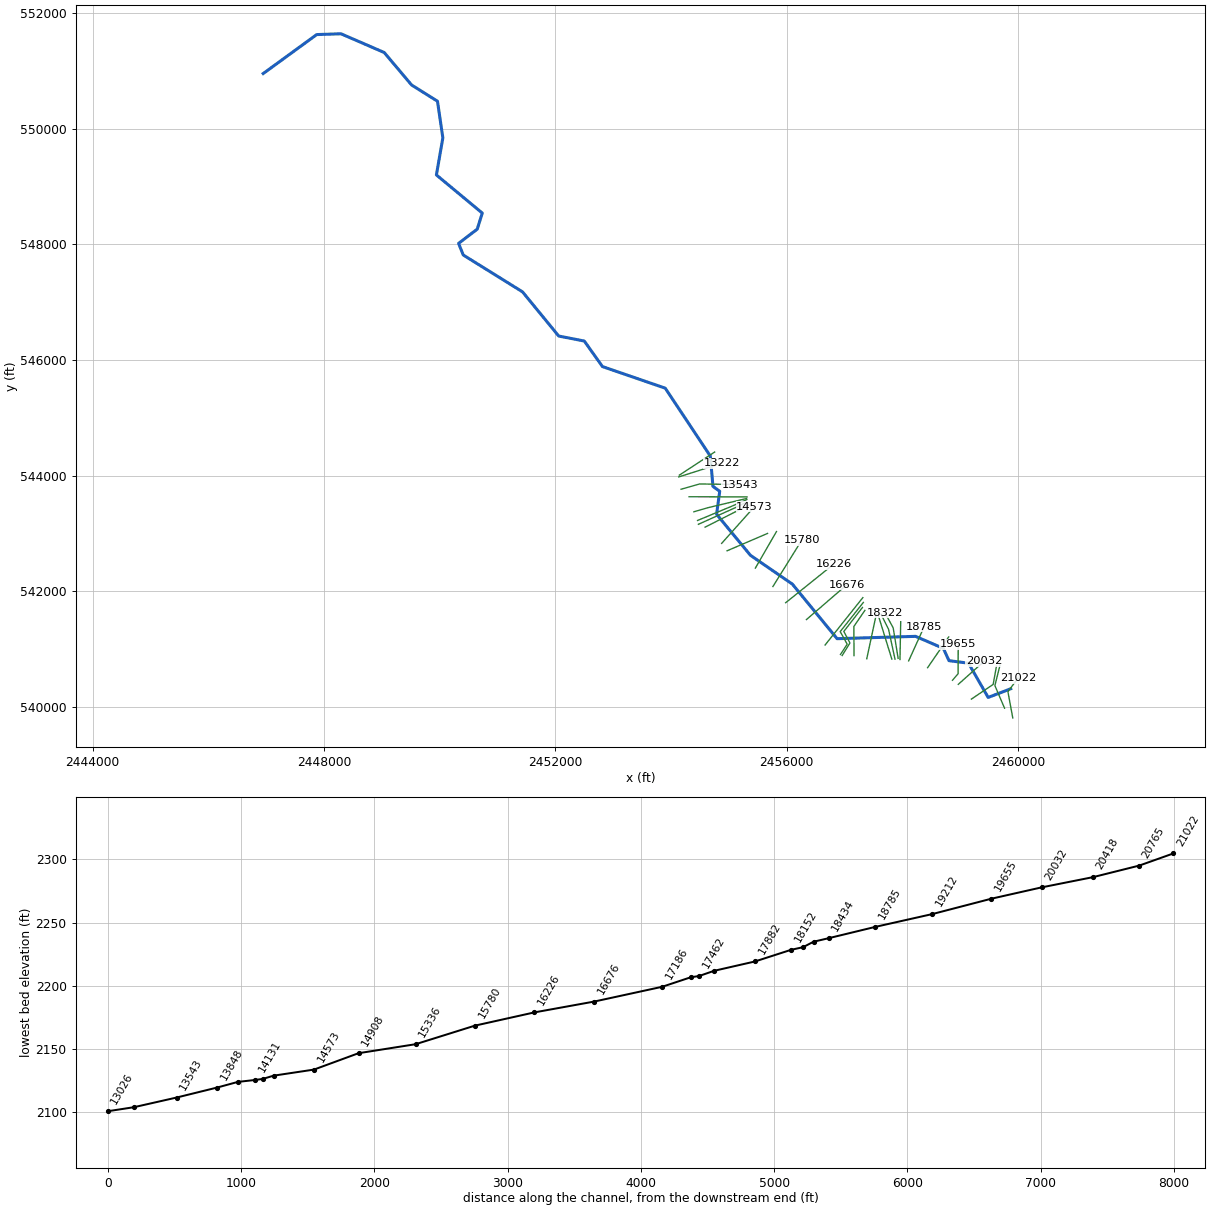
--- STONYRN.prj (project) ---

Proj Title=STONYRN
Current Plan=p01
Default Exp/Contr=0,0
English Units
Geom File=g01
Flow File=f01
Plan File=p01
BEGIN DESCRIPTION:
Stream Name: Stony Run
Flood Zone: Approximate
Pendleton County, West Virginia
HEC-RAS Version: 5.0.7
Hydrology Method:
Regression equation
END DESCRIPTION:
DSS File=dss
DSS Export Rating Curves= 0
DSS Export Rating Curve Sorted= 0
DSS Export Volume Flow Curves= 0
DXF OffsetX= 0
DXF OffsetY= 0
DXF ScaleX= 0
DXF ScaleY= 0

--- STONYRN.p01 (plan) ---

Plan Title=Floodplain
Program Version=5.07
Short Identifier=Floodplain
Geom File=g01
Flow File=f01
Subcritical Flow
K Sum by GR= 0
Std Step Tol= 0.01
Critical Tol= 0.01
Num of Std Step Trials= 20
Max Error Tol= 0.3
Flow Tol Ratio= 0.001
Split Flow NTrial= 30
Split Flow Tol= 0.02
Split Flow Ratio= 0.02
Log Output Level= 0
Friction Slope Method= 1
Unsteady Friction Slope Method= 2
Unsteady Bridges Friction Slope Method= 1
Parabolic Critical Depth
Global Vel Dist= 0 , 0 , 0
Global Log Level= 0
CheckData=True
Encroach Param=-1 ,0,0, 0
Computation Interval=0.1SEC
Output Interval=1MIN
Instantaneous Interval=Max Profile
Mapping Interval=1HOUR
Computation Time Step Use Courant=        0
Computation Time Step Use Time Series=    0
Computation Time Step Count To Double=0
Computation Time Step Max Doubling=0
Computation Time Step Max Halving=0
Computation Time Step Residence Courant=0
Run HTab= 0
Run UNet= 0
Run Sediment= 0
Run PostProcess= 0
Run WQNet= 0
Run RASMapper= 0
UNET Theta= 0
UNET Theta Warmup= 0
UNET ZTol= 0
UNET ZSATol= 0
UNET MxIter= 0
UNET Max Iter WO Improvement= 0
UNET MaxInSteps= 0
UNET DtIC= 0
UNET DtMin= 0
UNET MaxCRTS= 0
UNET WFStab= 0
UNET SFStab= 0
UNET WFX= 1
UNET SFX= 1
UNET 1D Methodology=Finite Difference
UNET DSS MLevel= 1
UNET Pardiso=0
UNET DZMax Abort= 0
UNET Use Existing IB Tables= 0
UNET Froude Reduction=False
UNET Froude Limit= 0
UNET Froude Power= 0
UNET D1 Cores= 0
UNET D2 Coriolis=0
UNET D2 Cores= 0
UNET D2 Theta= 1
UNET D2 Theta Warmup= 1
UNET D2 Z Tol= 0.01
UNET D2 Volume Tol= 0.01
UNET D2 Max Iterations= 20
UNET D2 Equation= 0
UNET D2 RampUpFraction=0.1
UNET D2 TimeSlices= 1
UNET D2 BCVolumeCheck=0
UNET D1D2 MaxIter= 0
UNET D1D2 ZTol=0.01
UNET D1D2 QTol=0.1
UNET D1D2 MinQTol=1
DSS File=dss
Write IC File= 0
Write IC File at Fixed DateTime=0
Write IC File at Sim End=0
Echo Input=False
Echo Parameters=False
Echo Output=False
Write Detailed= 0
HDF Write Warmup=0
HDF Write Time Slices=0
HDF Flush=0
HDF Face Node Velocities=0
HDF Compression= 1
HDF Chunk Size= 1
HDF Spatial Parts= 1
HDF Use Max Rows=0
HDF Fixed Rows= 1
Calibration Method= 0
Calibration Iterations= 20
Calibration Max Change=0.05
Calibration Tolerance=0.2
Calibration Maximum=1.5
Calibration Minimum=0.5
Calibration Optimization Method= 1
WQ AD Non Conservative
WQ ULTIMATE=-1
WQ Max Comp Step=1HOUR
WQ Output Interval=15MIN
WQ Output Selected Increments= 0
WQ Output face flow=0
WQ Output face velocity=0
WQ Output face area=0
WQ Output face dispersion=0
WQ Output cell volume=0
WQ Output cell surface area=0
WQ Output cell continuity=0
WQ Output cumulative cell continuity=0
WQ Output face conc=0
WQ Output face dconc_dx=0
WQ Output face courant=0
WQ Output face peclet=0
WQ Output face adv mass=0
WQ Output face disp mass=0
WQ Output cell mass=0
WQ Output cell source sink temp=0
WQ Output nsm pathways=0
WQ Output nsm derived pathways=0
WQ Output MaxMinRange=-1
WQ Daily Max Min Mean=-1
WQ Daily Range=0
WQ Daily Time=0
WQ Create Restart=0
WQ Fixed Restart=0
WQ System Summary=0
WQ Write To DSS=0
WQ Use Fixed Temperature=0
Sorting and Armoring Iterations= 10
XS Update Threshold= 0.02
Bed Roughness Predictor= 0
Hydraulics Update Threshold= 0.02
Energy Slope Method= 1
Volume Change Method= 1
Sediment Retention Method= 0
XS Weighting Method= 0
Number of US Weighted Cross Sections= 1
Number of DS Weighted Cross Sections= 1
Upstream XS Weight=0
Main XS Weight=1
Downstream XS Weight=0
Number of DS XS's Weighted with US Boundary= 1
Upstream Boundary Weight= 1
Weight of XSs Associated with US Boundary= 0
Number of US XS's Weighted with DS Boundary= 1
Downstream Boundary Weight= 0.5
Weight of XSs Associated with DS Boundary= 0.5
Percentile Method= 0
Sediment Output Level= 3
Mass or Volume Output= 0
Output Increment Type= 1
Profile and TS Output Increment= 1
XS Output Flag= 0
XS Output Increment= 10
Write Gradation File= 0
Read Gradation Hotstart= 0
Write HDF5 File= 1
Write Binary Output= 1
Write DSS Sediment File= 0
SV Curve= 0
Specific Gage Flag= 0

--- STONYRN.f01 (steady flow) ---

Flow Title=Flows
Program Version=5.07
Number of Profiles= 6
Profile Names=P100yr,P10yr,P25yr,P50yr,P500yr,P101yr
River Rch & RM=STONYRN,Main            ,21022
     953     442     627     785    1404    1160
River Rch & RM=STONYRN,Main            ,14270
    1060     491     697     873    1563    1290
River Rch & RM=STONYRN,Main            ,9177
    1185     548     779     976    1750    1442
River Rch & RM=STONYRN,Main            ,3587
    1832     842    1200    1507    2719    2230
Boundary for River Rch & Prof#=STONYRN,Main            , 1
Up Type= 0
Dn Type= 3
Dn Slope=0.01098
Boundary for River Rch & Prof#=STONYRN,Main            , 2
Up Type= 0
Dn Type= 3
Dn Slope=0.01098
Boundary for River Rch & Prof#=STONYRN,Main            , 3
Up Type= 0
Dn Type= 3
Dn Slope=0.01098
Boundary for River Rch & Prof#=STONYRN,Main            , 4
Up Type= 0
Dn Type= 3
Dn Slope=0.01098
Boundary for River Rch & Prof#=STONYRN,Main            , 5
Up Type= 0
Dn Type= 3
Dn Slope=0.01098
Boundary for River Rch & Prof#=STONYRN,Main            , 6
Up Type= 0
Dn Type= 3
Dn Slope=0.01098
DSS Import GetInterval= 0
DSS Import GetPeak= 0
DSS Import FillOption= 0

--- STONYRN.g01 (geometry) ---

Geom Title=Geometry
Program Version=5.07

River Reach=STONYRN         ,Main
Reach XY= 30
     2459875.168       540317.97      2459483.94      540167.882
     2459144.363      540760.165     2458806.895      540803.839
     2458709.737      541015.799     2458228.983      541224.183
     2456872.209      541183.749     2456100.013      542126.439
     2455374.579      542625.127     2454788.969      543334.388
      2454843.32      543731.942     2454726.516      543816.421
     2454680.292      544341.681     2453901.721      545514.465
     2452815.643      545888.341      2452502.35      546329.425
     2452059.565      546416.048     2451433.404       547180.16
     2450409.509      547816.6612450328.72873104548018.052493353
2450650.67607418548263.7314389832450738.20271125548541.566415147
2449944.95530234549201.158642578     2450056.523      549842.455
      2449963.56       550475.74      2449515.89      550756.442
     2449042.277      551318.215     2448295.441      551641.569
     2447875.548      551627.853     2446950.827       550953.91

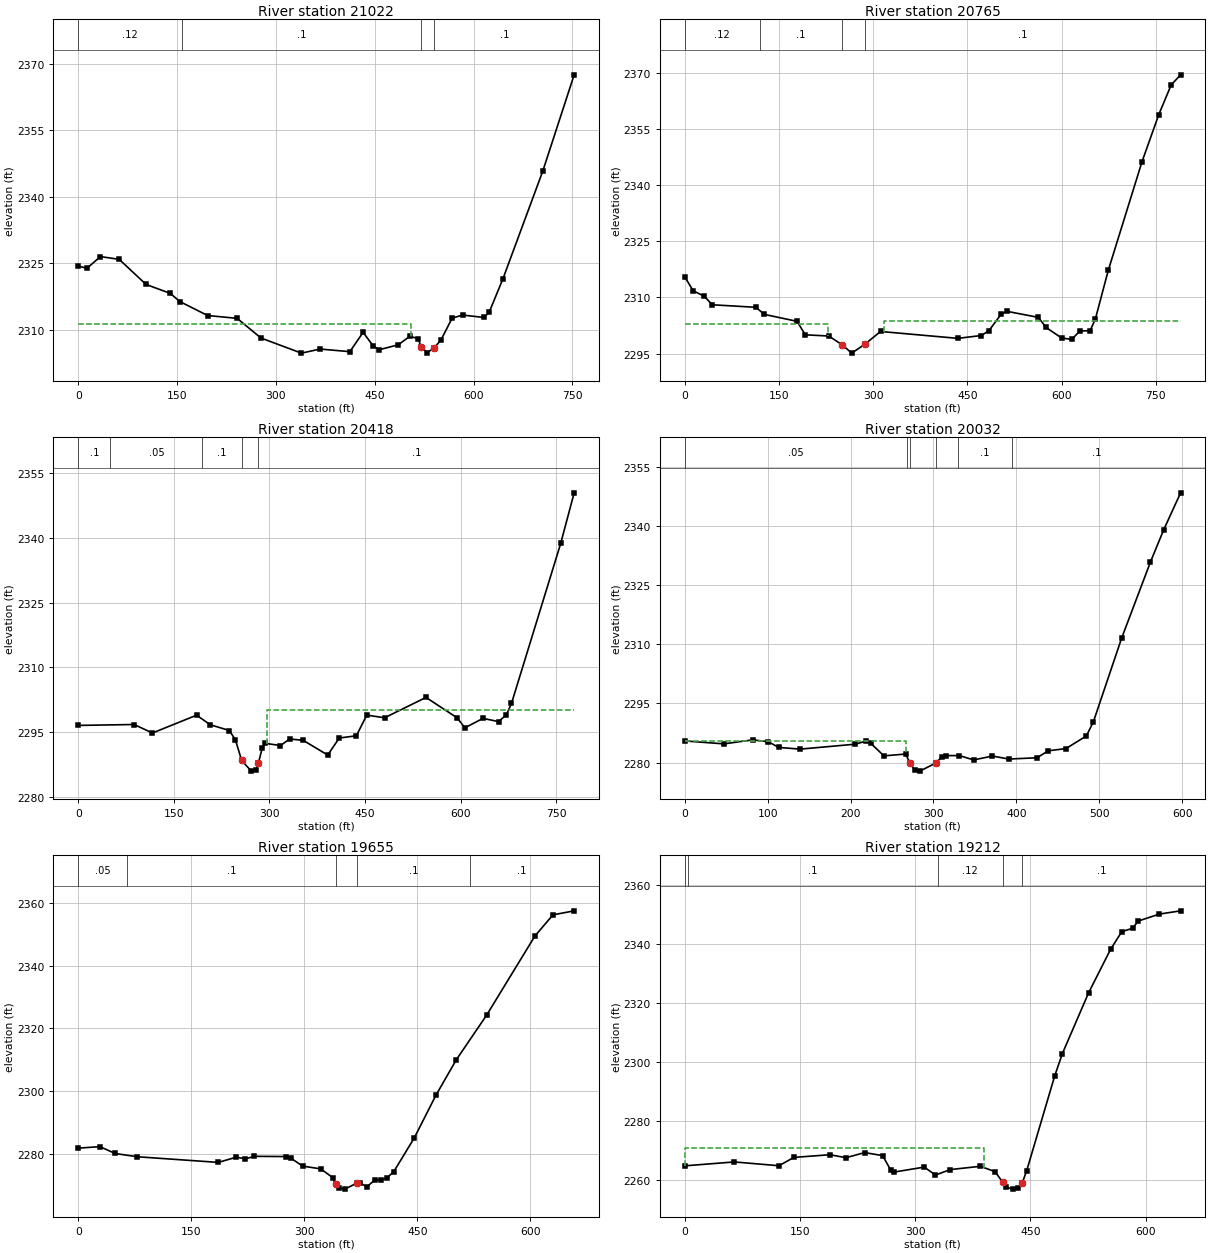
Type RM Length L Ch R = 1 ,21022   ,239.5,256.5,268.9
XS GIS Cut Line= 3
  2459909.702802539813.7498952462459825.62125966540267.128859215
2459999.94010361540500.904256568
#Sta/Elev= 30
       0 2324.37    13.4  2323.9    33.7 2326.52    62.2  2325.9     103 2320.23
   139.5 2318.23   154.5 2316.35   196.4 2313.22   241.2 2312.58   277.4 2308.14
   338.8 2304.73   367.2 2305.65   412.3 2305.06   432.4 2309.43   447.2 2306.45
   456.5 2305.49   485.8 2306.61   503.1 2308.52   515.7 2308.03   520.7 2306.06
   529.9 2304.85   540.6 2305.98   550.6 2307.71   567.5 2312.62   583.4 2313.33
   615.5 2312.78   623.6 2313.91   644.7 2321.54   705.3 2345.91   752.7 2367.55
#Mann= 4 ,-1 , 0
       0     .12       0  157.33      .1       0   520.7    .045       0
   540.6      .1       0
#XS Ineff= 2 , 0
          505.61 2311.32
Permanent Ineff=
       F       F
Bank Sta=520.7,540.6
XS Rating Curve= 0 ,0
Exp/Cntr=0.3,0.1

Type RM Length L Ch R = 1 ,20765   ,372.7,346.7,317.6
XS GIS Cut Line= 3
2459767.58160217539982.4294634022459600.53460743540372.737051724
     2459689.269      540726.504
#Sta/Elev= 30
       0 2315.53    13.6 2311.76      31 2310.33      44 2308.03   113.4 2307.35
   126.7 2305.46   178.9  2303.6   191.9    2300   229.5 2299.67   250.8  2297.3
   265.9  2295.1   286.8 2297.49   311.8 2300.89   434.7 2299.05   472.1 2299.81
   484.2 2301.09     504 2305.59   513.4 2306.26   562.9 2304.66   575.2 2301.96
     600 2299.13   616.1 2298.78   628.8 2301.01   645.3  2301.1   653.6 2304.21
   674.2 2317.27   727.8 2346.26   754.5 2358.87   774.3 2366.84   789.3 2369.52
#Mann= 4 ,-1 , 0
       0     .12       0  119.23      .1       0   250.8    .045       0
   286.8      .1       0
#XS Ineff= 2 , 0
             228 2302.78  317.74         2303.58
Permanent Ineff=
       F       F
Bank Sta=250.8,286.8
XS Rating Curve= 0 ,0
Exp/Cntr=0.3,0.1

Type RM Length L Ch R = 1 ,20418   ,383.1,386.3,387.5
XS GIS Cut Line= 3
 2459194.0964928540139.1376037532459570.68009396540392.811424879
2459628.13780106 540711.63601061
#Sta/Elev= 30
       0 2296.56    87.6 2296.77   116.5  2294.8   185.7 2298.93   207.2 2296.71
   237.1 2295.38   246.7 2293.18   256.4 2288.43   271.6 2285.96   278.8 2286.29
   282.7 2287.83   288.5 2291.21   293.1 2292.41   317.3  2291.9   331.7 2293.41
   352.9  2293.1   391.4 2289.69   409.5 2293.64   436.3 2294.15   452.7 2298.95
   480.6 2298.33   545.6 2303.05   594.4 2298.32   606.6 2296.01     635 2298.19
   659.4 2297.45   671.6    2299   679.7 2301.66   756.9 2338.76     778 2350.49
#Mann= 5 ,-1 , 0
       0      .1       0   50.45     .05       0  194.67      .1       0
   256.4    .045       0   282.7      .1       0
#XS Ineff= 2 , 0
                          296.18         2300.13
Permanent Ineff=
       F       F
Bank Sta=256.4,282.7
XS Rating Curve= 0 ,0
Exp/Cntr=0.3,0.1

Type RM Length L Ch R = 1 ,20032   ,361.5,376.8,391.8
XS GIS Cut Line= 2
2458967.36982165540394.2051087932459413.92773852540792.156711351
#Sta/Elev= 30
       0  2285.5    47.4 2284.76    82.3 2285.78     101 2285.28   113.4 2283.86
   139.3 2283.43   205.4 2284.67   218.8 2285.46   224.2 2284.95   240.3 2281.72
   266.4 2282.18   271.6 2279.97   277.6 2278.08   283.6 2277.85   303.2 2279.94
   309.9 2281.45   315.3 2281.79   331.3 2281.79   348.5 2280.69   371.2 2281.67
     391 2280.91     425 2281.24   438.5    2283   459.9 2283.57   484.5 2286.78
     493 2290.42     527 2311.58   561.7 2330.85   577.8 2339.08   598.1 2348.39
#Mann= 6 ,-1 , 0
       0     .05       0   268.3      .1       0   271.6    .045       0
   303.2      .1       0  329.86      .1       0  394.63      .1       0
#XS Ineff= 2 , 0
          266.43 2285.42
Permanent Ineff=
       F       F
Bank Sta=271.6,303.2
XS Rating Curve= 0 ,0
Exp/Cntr=0.3,0.1

Type RM Length L Ch R = 1 ,19655   ,450.4,443.5,427.4
XS GIS Cut Line= 3
2458867.55412754  540464.97881612458964.72521446540578.185614501
2458966.72697112541087.207980745
#Sta/Elev= 30
       0 2281.92    28.9  2282.4      49 2280.22    78.6 2279.18   185.9 2277.39
   209.9 2279.05   221.9 2278.52   233.9 2279.32   275.4 2279.25   281.9 2278.78
   297.9 2276.21   321.9 2275.33   337.9 2272.53   341.9 2270.43   345.9 2269.27
   353.9 2268.89   369.9 2270.82   373.9 2270.88     383 2269.62   393.9 2271.84
   401.9 2271.75   409.9 2272.48   418.9 2274.49   445.9 2285.12   474.6 2298.68
   501.9 2310.07   541.9 2324.16   606.1 2349.36     630  2356.1   658.2 2357.39
#Mann= 5 ,-1 , 0
       0     .05       0    64.7      .1       0   341.9    .045       0
   369.9      .1       0  520.13      .1       0
Bank Sta=341.9,369.9
XS Rating Curve= 0 ,0
Exp/Cntr=0.3,0.1

Type RM Length L Ch R = 1 ,19212   ,423.4,426.9,428.8
XS GIS Cut Line= 2
2458436.99365346540681.7272385412458802.07847038541214.107379311
#Sta/Elev= 30
       0 2264.64    64.5 2265.97   122.7 2264.68   142.1 2267.51   189.1 2268.42
     210 2267.41   234.2 2269.14   257.7 2268.12   268.2 2263.16   271.9  2262.5
   311.8 2264.21   326.4 2261.52   345.8 2263.38   384.8 2264.48     404 2262.67
   413.7 2259.16   418.5 2257.39   427.5 2256.73   433.7 2257.02   439.4 2258.85
   445.2 2263.04   481.6 2295.19   491.6 2302.79   525.7 2323.43   554.3 2338.19
   568.9 2344.22   583.3 2345.39   590.1 2347.81   617.8 2350.19   645.5  2351.3
#Mann= 5 ,-1 , 0
       0     .05       0    4.88      .1       0  329.35     .12       0
   413.7    .045       0   439.4      .1       0
#XS Ineff= 2 , 0
          390.17 2270.75
Permanent Ineff=
       F       F
Bank Sta=413.7,439.4
XS Rating Curve= 0 ,0
Exp/Cntr=0.3,0.1

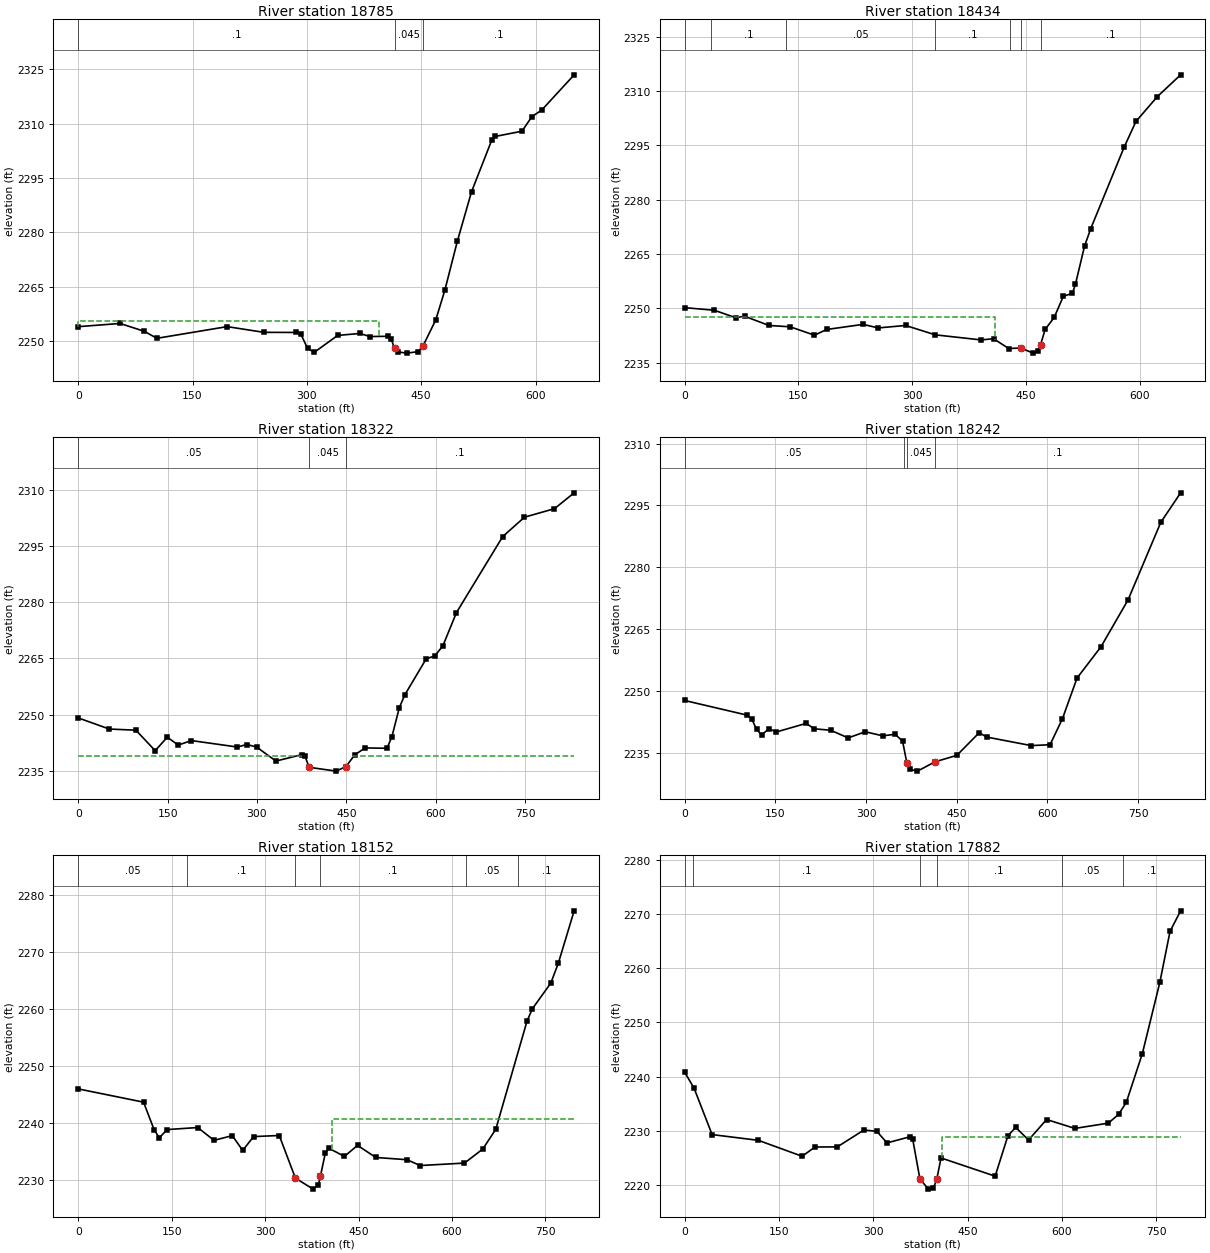
Type RM Length L Ch R = 1 ,18785   ,339.6,350.7,357.8
XS GIS Cut Line= 2
2458110.06935279540800.8891069852458378.93690893541393.428272326
#Sta/Elev= 30
       0 2253.92    54.9  2254.8    86.6 2252.65   103.2  2250.7   195.4 2253.93
   243.7 2252.35     286 2252.32   292.1 2251.87   300.9 2247.93   309.7 2246.83
   340.4  2251.5   369.5 2252.04   382.7 2251.19   406.3 2251.26   410.7 2250.46
   415.1 2247.93   419.5 2246.94   431.1 2246.61   445.8 2247.01   452.2 2248.52
   469.1 2255.77     481 2263.96   497.5 2277.57   516.1 2291.21   542.5 2305.39
   546.9 2306.44   582.2  2307.9   595.2  2311.9   608.4 2313.79   650.7 2323.47
#Mann= 3 ,-1 , 0
       0      .1       0   415.1    .045       0   452.2      .1       0
#XS Ineff= 2 , 0
          394.63 2255.58
Permanent Ineff=
       F       F
Bank Sta=415.1,452.2
XS Rating Curve= 0 ,0
Exp/Cntr=0.3,0.1

Type RM Length L Ch R = 1 ,18434   ,111.5,112.2,115.1
XS GIS Cut Line= 2
     2457959.671      540823.7762457972.17020601541477.460657383
#Sta/Elev= 30
       0 2250.21    39.1 2249.49    67.1 2247.44    79.1 2247.83   111.1 2245.29
   139.1 2244.92   171.1  2242.6   187.1 2244.18   235.2 2245.59   255.2 2244.61
   291.2 2245.29   330.4  2242.7   390.8  2241.3   407.2 2241.63   427.2 2238.92
   443.2 2239.07   459.2 2237.65   465.4 2238.22   469.1 2239.96   475.2 2244.19
   487.2 2247.54   499.2 2253.36   511.2 2254.17   515.2 2256.73   527.2 2267.24
   535.2 2271.98   579.2 2294.47   594.9 2301.64   623.2 2308.52   653.8 2314.52
#Mann= 7 ,-1 , 0
       0     .05       0   35.14      .1       0  133.56     .05       0
   330.4      .1       0  428.82      .1       0   443.2    .045       0
   469.1      .1       0
#XS Ineff= 2 , 0
           408.9 2247.76
Permanent Ineff=
       F       F
Bank Sta=443.2,469.1
XS Rating Curve= 0 ,0
Exp/Cntr=0.5,0.3

Type RM Length L Ch R = 1 ,18322   ,78.4,79.9,87
XS GIS Cut Line= 3
2457927.84249735540843.3360941642457842.11910477  541371.5098687
     2457698.932      541632.007
#Sta/Elev= 30
       0 2249.09    52.2 2246.12    96.8 2245.81   129.2 2240.34   149.5 2243.94
   167.9 2241.84     190 2243.04     267 2241.32     283 2241.99   299.4 2241.31
   331.8 2237.57   376.4 2239.32   380.5 2238.91   387.6  2235.9   432.9 2234.88
   449.4  2236.1   464.3 2239.27   481.7 2241.08   518.2 2240.98   526.4 2244.05
   538.9 2251.82   548.1 2255.25   584.2 2264.92   598.3 2265.62     612 2268.35
   634.8 2277.22   712.4 2297.52   748.9 2302.69   799.3 2304.97   832.3  2309.2
#Mann= 3 ,-1 , 0
       0     .05       0   387.6    .045       0   449.4      .1       0
#XS Ineff= 2 , 0
          379.82 2239.01  461.29            2239
Permanent Ineff=
       F       F
Bank Sta=387.6,449.4
XS Rating Curve= 0 ,0
Exp/Cntr=0.5,0.3

Type RM Length L Ch R = 1 ,18242   ,84.2,90.4,89.7
XS GIS Cut Line= 3
2457873.35180106540830.5800941642457762.22888992541346.028255968
     2457631.412      541608.174
#Sta/Elev= 30
       0 2247.68   102.6 2244.15   110.8 2243.24     119 2240.65   127.2 2239.33
   139.4 2240.81   151.7 2240.04   200.8 2242.12   214.5 2240.81   241.5 2240.46
   270.4  2238.6   298.7 2240.09   327.7  2239.1   348.1 2239.49   360.4 2237.81
   367.4  2232.6   372.7 2230.97     385 2230.54   414.3 2232.81   450.2 2234.37
   487.2 2239.87   499.5 2238.81     573 2236.74   604.3 2236.94   624.7 2243.21
     649 2253.13   688.6 2260.72   733.3 2272.08   787.5  2290.9   820.3 2298.07
#Mann= 4 ,-1 , 0
       0     .05       0  362.26      .1       0   367.4    .045       0
   414.3      .1       0
Bank Sta=367.4,414.3
XS Rating Curve= 0 ,0
Exp/Cntr=0.5,0.3

Type RM Length L Ch R = 1 ,18152   ,280.6,269.9,255.1
XS GIS Cut Line= 2
2457818.59528473540830.6473471062457583.24841794541591.103408018
#Sta/Elev= 30
       0 2246.02   104.9 2243.69   121.7 2238.89   130.1 2237.42   142.6 2238.88
   191.9 2239.24     218 2236.99   247.3 2237.82     264 2235.22   281.5 2237.65
   322.7 2237.84   348.6 2230.36   377.1 2228.43   385.5 2229.16   388.7 2230.68
   396.6 2234.75   402.2 2235.61   427.3 2234.17   448.3 2236.11   477.6 2233.99
   527.8 2233.59   548.8 2232.57     620    2233   649.3 2235.46   670.2 2238.93
   720.4 2257.93   728.8 2260.06   758.6  2264.6   770.7 2268.12     796 2277.27
#Mann= 6 ,-1 , 0
       0     .05       0  175.34      .1       0   348.6    .045       0
   388.7      .1       0  621.97     .05       0  706.46      .1       0
#XS Ineff= 2 , 0
                          407.05         2240.65
Permanent Ineff=
       F       F
Bank Sta=348.6,388.7
XS Rating Curve= 0 ,0
Exp/Cntr(USF)=0,0
Exp/Cntr=0.3,0.1

Type RM Length L Ch R = 1 ,17882   ,302.4,306.1,309.1
XS GIS Cut Line= 2
2457385.25209211540836.3039819112457550.53041119541607.288453947
#Sta/Elev= 30
       0 2240.81    14.9 2237.88    43.6 2229.31   117.2 2228.25   186.7 2225.31
   207.2 2227.02   242.6 2227.04   284.9 2230.15   305.4 2229.92   321.7 2227.78
   358.6 2228.92   362.6 2228.42     374 2221.13   387.5 2219.25   395.4 2219.37
   400.9 2221.15   407.6    2225   493.6 2221.64     514 2229.12   526.3 2230.64
   546.7 2228.31   575.4 2232.09   620.4 2230.45   673.5 2231.42   689.9 2233.04
   702.2 2235.27   727.7 2244.27   755.4 2257.37   771.7 2266.81   788.5 2270.59
#Mann= 6 ,-1 , 0
       0     .05       0   13.09      .1       0     374    .045       0
   400.9      .1       0   599.2     .05       0  696.88      .1       0
#XS Ineff= 2 , 0
                          409.16         2228.94
Permanent Ineff=
       F       F
Bank Sta=374,400.9
XS Rating Curve= 0 ,0
Exp/Cntr=0.3,0.1

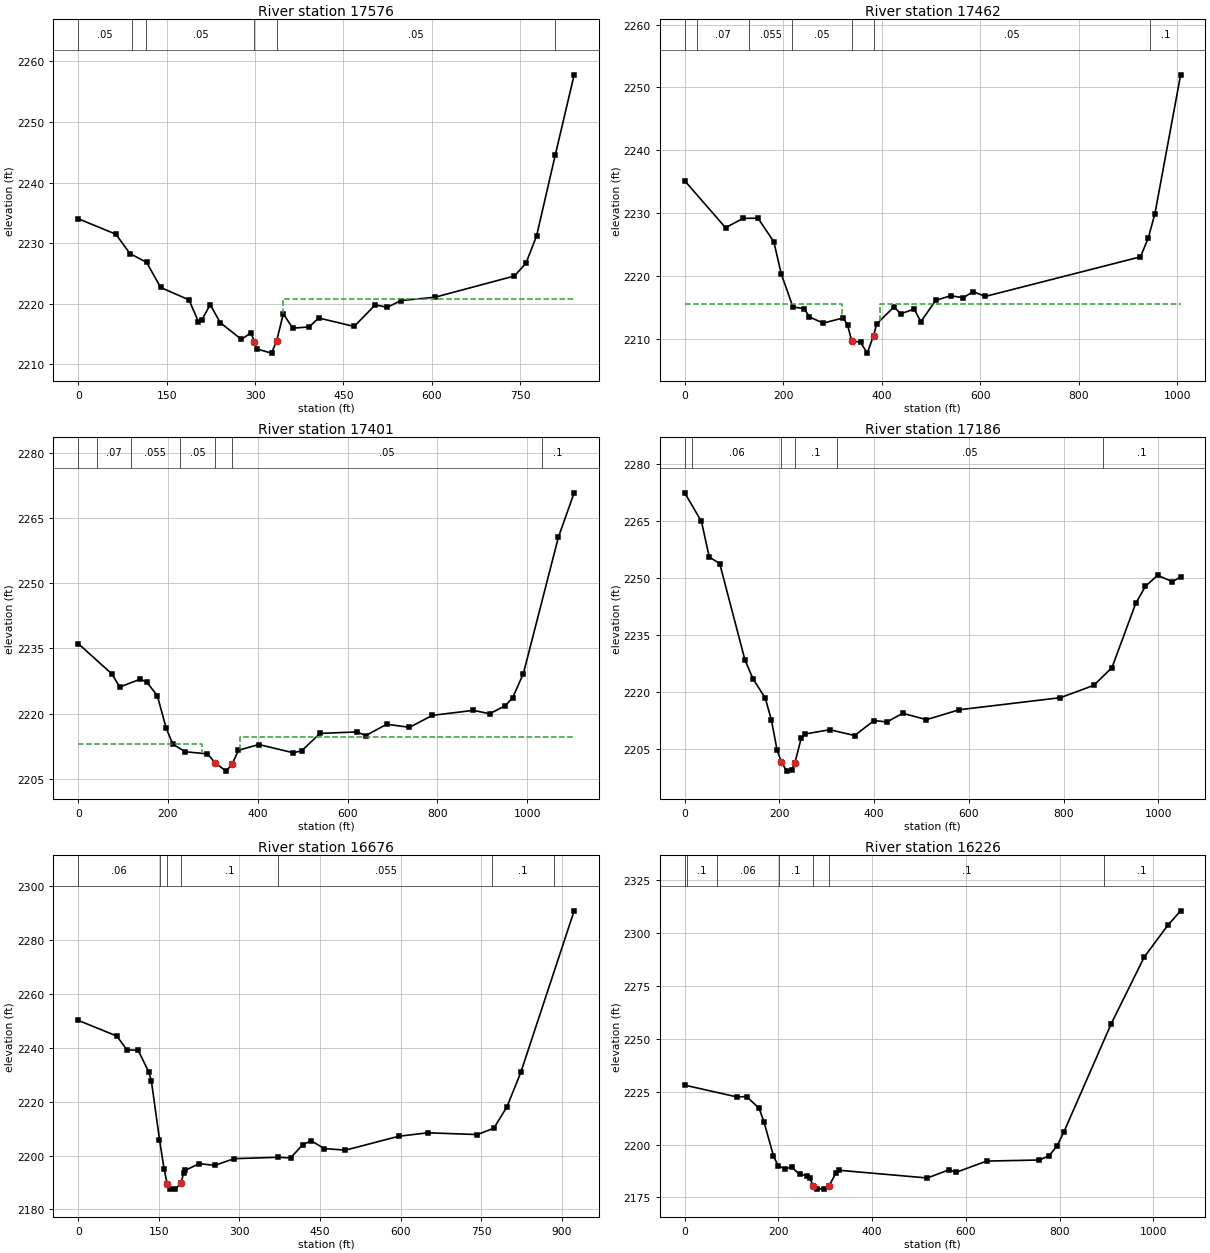
Type RM Length L Ch R = 1 ,17576   ,105.8,113.5,131.4
XS GIS Cut Line= 3
     2457164.864540890.9951768162457162.78195625541395.675804421
2457353.01387584541673.430393097
#Sta/Elev= 30
       0 2234.05    63.9 2231.49    87.9 2228.28   115.9 2226.86   139.9  2222.7
   187.9 2220.66   203.9 2217.06   209.2 2217.26   223.9 2219.87     241 2216.89
   276.9 2214.14   292.8 2215.21     299 2213.78   303.9 2212.53   327.9 2211.87
   336.6 2213.88   347.9 2218.36   363.9 2215.98   391.9  2216.2   407.9 2217.67
   468.1 2216.27   503.9 2219.84   524.2 2219.43   547.4 2220.54   605.5  2221.1
     740  2224.6   759.5 2226.69   777.5 2231.19   809.2 2244.53   841.3 2257.79
#Mann= 6 ,-1 , 0
       0     .05       0   91.51      .1       0  115.31     .05       0
     299    .045       0   336.6     .05       0   809.2      .1       0
#XS Ineff= 2 , 0
                          348.04         2220.82
Permanent Ineff=
       F       F
Bank Sta=299,336.6
XS Rating Curve= 0 ,0
Exp/Cntr=0.5,0.3

Type RM Length L Ch R = 1 ,17462   ,55.5,61.2,55.1
XS GIS Cut Line= 4
2456959.98186637540892.5006327392457094.96401433541109.238339814
2456988.51587241541308.816891187 2457310.7646986541723.192217907
#Sta/Elev= 30
       0 2235.16    82.9 2227.69   118.7 2229.18   148.9 2229.19   180.9 2225.45
     196 2220.34   219.6 2215.09   243.1 2214.78   252.6  2213.5   281.3 2212.51
   321.8 2213.33   330.6 2212.18   338.8 2209.71   356.9 2209.44   370.5 2207.73
   383.3 2210.52   389.8 2212.39   424.9 2215.09   438.5 2213.98   465.7 2214.75
   479.3 2212.72   509.5 2216.13   539.9 2216.86   565.2 2216.55   585.5 2217.51
     610 2216.75     925 2223.05   940.7 2226.01   954.3  2229.9  1006.5 2252.01
#Mann= 7 ,-1 , 0
       0     .06       0   24.78     .07       0   130.8    .055       0
  218.25     .05       0   338.8    .045       0   383.3     .05       0
  944.44      .1       0
#XS Ineff= 2 , 0
          319.93 2215.52  396.06         2215.56
Permanent Ineff=
       F       F
Bank Sta=338.8,383.3
XS Rating Curve= 0 ,0
Exp/Cntr(USF)=0,0
Exp/Cntr=0.5,0.3

Type RM Length L Ch R = 1 ,17401   ,242.3,215.4,191.8
XS GIS Cut Line= 4
2456930.59174434540911.0302081572457047.17032673541088.354921621
2456926.20250588541306.1100031052457326.17685904541810.257281897
#Sta/Elev= 30
       0  2236.1    75.1 2229.13    92.4 2226.12   138.6 2227.94     153 2227.19
   176.2 2224.16   196.1 2216.61   210.8    2213   238.2 2211.24   287.9 2210.75
   305.6 2208.63   329.5 2206.78   343.2 2208.44     357 2211.59   402.5  2212.9
   479.3 2210.99   498.1 2211.49   538.9 2215.46   620.6 2215.79     641 2214.97
   687.2 2217.56     738 2216.85   789.1 2219.61   880.5 2220.75   916.7 2219.98
   951.3 2221.81   967.8 2223.62   991.8 2229.23  1069.9  2260.6  1104.9 2270.78
#Mann= 7 ,-1 , 0
       0     .06       0   41.36     .07       0  117.06    .055       0
  226.07     .05       0   305.6    .045       0   343.2     .05       0
 1032.91      .1       0
#XS Ineff= 2 , 0
          276.16 2213.05  359.96         2214.74
Permanent Ineff=
       F       F
Bank Sta=305.6,343.2
XS Rating Curve= 0 ,0
Exp/Cntr(USF)=0,0
Exp/Cntr=0.5,0.3

Type RM Length L Ch R = 1 ,17186   ,512.1,509.7,504.9
XS GIS Cut Line= 2
2456664.68214589541074.3343766572457317.01840716 541893.03952785
#Sta/Elev= 30
       0  2272.3    35.4 2264.78    51.9 2255.42    73.9 2253.74   127.1 2228.45
   143.9 2223.54   170.2 2218.36     183 2212.64   195.1 2204.73     204 2201.69
   215.3 2199.22   225.7 2199.53   232.4  2201.3   246.2 2207.99   253.6 2208.96
   306.4 2210.09   358.7 2208.57   399.6 2212.49     427 2212.14   460.1  2214.4
   510.4 2212.74   579.7 2215.34   793.2 2218.51   863.4 2221.74     902 2226.43
     952 2243.26   972.5 2247.76   998.2 2250.65  1029.4 2248.97  1046.8 2250.22
#Mann= 6 ,-1 , 0
       0      .1       0   15.44     .06       0     204    .045       0
   232.4      .1       0  320.73     .05       0  882.22      .1       0
Bank Sta=204,232.4
XS Rating Curve= 0 ,0
Exp/Cntr=0.3,0.1

Type RM Length L Ch R = 1 ,16676   ,449.5,449.9,448.4
XS GIS Cut Line= 2
2456342.39031321541513.9412047892457040.89010838 542116.45242164
#Sta/Elev= 30
       0 2250.18    71.8 2244.35    90.3  2239.3   111.7    2239   131.4 2230.93
   136.2 2227.53   151.2 2205.92   159.7 2195.11   165.4 2189.59   171.1 2187.77
   180.1 2187.54   191.3 2189.74   195.9 2193.46   199.5 2194.54   224.9    2197
     254 2196.35   290.2 2198.85   372.5 2199.36   395.1 2199.11   417.8 2204.09
   433.6 2205.44   457.5 2202.61     497    2202   596.5 2207.17   650.4 2208.44
   742.5 2207.79   773.1 2210.15   797.6 2218.13   823.4 2230.94   922.5 2290.82
#Mann= 7 ,-1 , 0
       0     .06       0  152.61      .1       0   165.4    .045       0
   191.3      .1       0   372.5    .055       0  770.53      .1       0
   884.7      .1       0
Bank Sta=165.4,191.3
XS Rating Curve= 0 ,0
Exp/Cntr=0.3,0.1

Type RM Length L Ch R = 1 ,16226   ,438.4,446,453.1
XS GIS Cut Line= 2
2455982.92051805541805.0119517962456808.40143698542467.446710777
#Sta/Elev= 30
       0 2228.15   111.6 2222.57   132.1 2222.73   158.8 2217.21   169.1 2210.84
   189.5  2194.7   199.8 2189.78   213.9 2188.69   228.8 2189.19   245.9 2185.87
   261.3 2185.38   266.5 2184.32   274.4 2180.48   281.9 2178.94     297 2179.08
   308.5  2180.6   322.7 2186.56   328.4 2187.89   517.8 2184.21   563.9 2188.07
   579.3 2186.89   644.3 2192.21   757.1 2192.72     778 2194.78   795.1 2199.51
   809.3 2206.02   910.5 2257.31   980.8 2288.77  1031.2 2303.84  1058.4 2310.64
#Mann= 7 ,-1 , 0
       0      .1       0     4.4      .1       0   69.43     .06       0
  201.56      .1       0   274.4    .045       0   308.5      .1       0
  894.23      .1       0
Bank Sta=274.4,308.5
XS Rating Curve= 0 ,0
Exp/Cntr=0.3,0.1

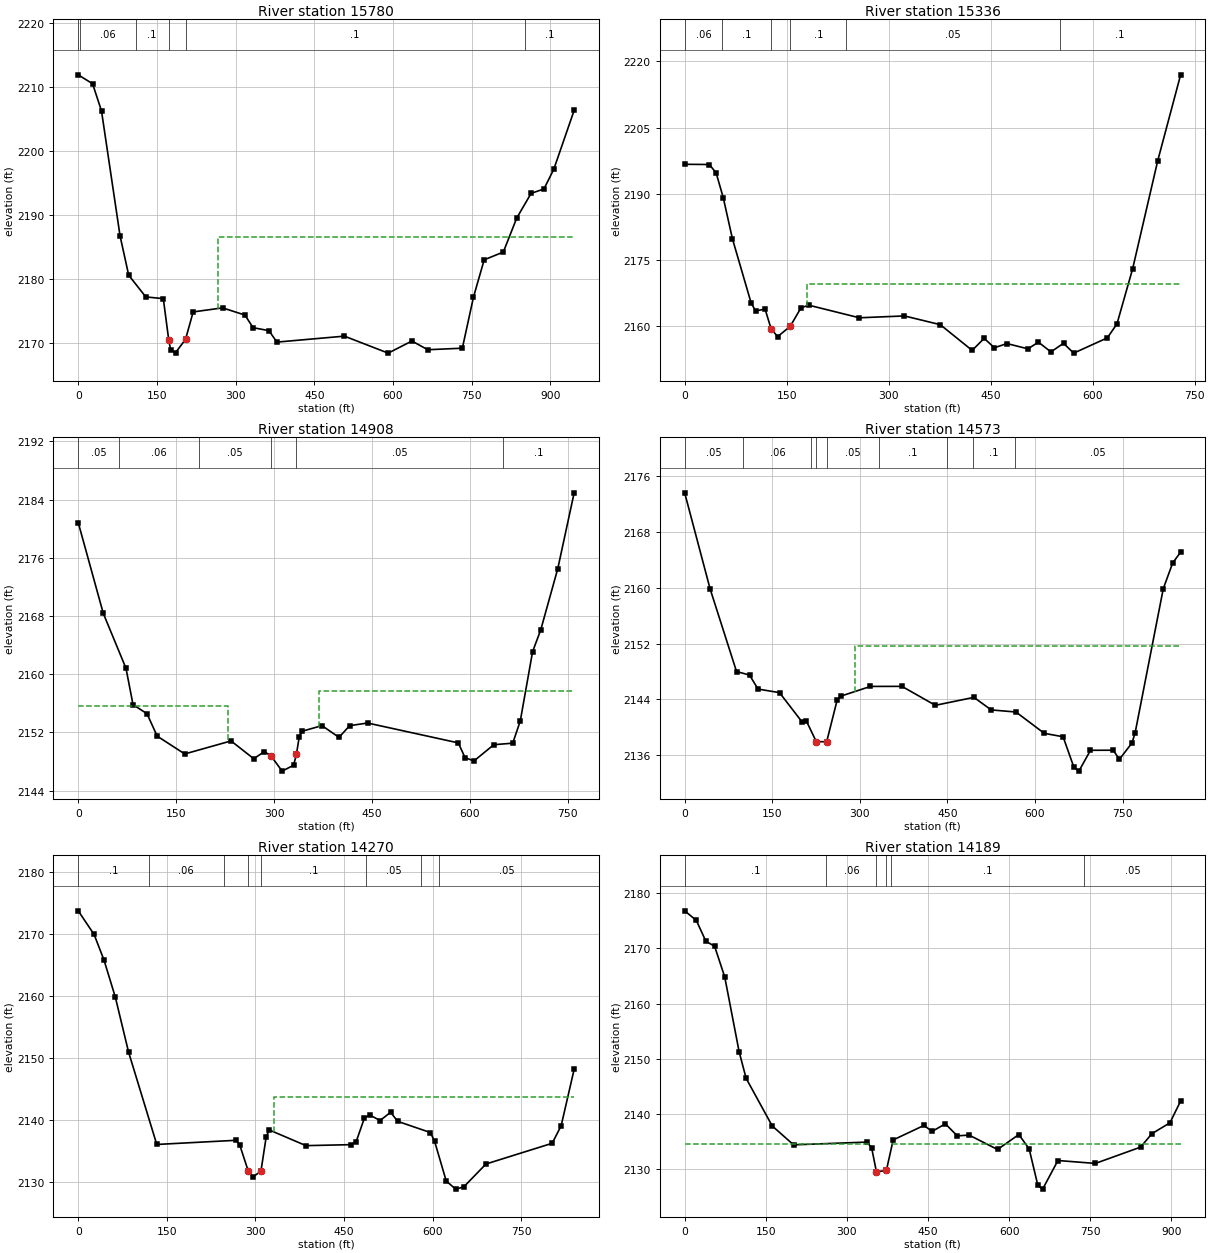
Type RM Length L Ch R = 1 ,15780   ,443.9,444.1,444.3
XS GIS Cut Line= 2
2455762.68932944542085.2098265242456262.08744178542887.828708354
#Sta/Elev= 30
       0 2211.89    27.4  2210.5    44.4 2206.25    79.7 2186.79    96.2 2180.63
   128.8 2177.24   162.2 2176.97   172.6 2170.49   176.3 2168.94   185.7 2168.56
   204.6 2170.63   219.1  2174.9   275.2 2175.53   317.8 2174.41   333.3 2172.44
   363.5 2171.98   378.7 2170.19   507.4 2171.12   590.8 2168.47   636.1 2170.36
   666.2    2169   732.2 2169.24   753.4 2177.21   773.8 2183.03   810.3 2184.24
   835.8 2189.54   863.3  2193.4   887.7 2194.08   906.5 2197.16   945.3 2206.35
#Mann= 6 ,-1 , 0
       0      .1       0    3.51     .06       0   109.5      .1       0
   172.6    .045       0   204.6      .1       0  851.49      .1       0
#XS Ineff= 2 , 0
                          265.56         2186.64
Permanent Ineff=
       F       F
Bank Sta=172.6,204.6
XS Rating Curve= 0 ,0
Exp/Cntr=0.3,0.1

Type RM Length L Ch R = 1 ,15336   ,439.8,428.5,412.6
XS GIS Cut Line= 2
2455459.61739231542404.5754283812455824.39090279543035.955567506
#Sta/Elev= 30
       0 2196.66    36.2 2196.61    46.2 2194.73    56.7  2189.1    70.2 2179.76
    97.7 2165.19   104.3 2163.38   118.2 2163.81     127 2159.36   136.6 2157.55
   155.1 2159.87   170.9 2164.06   182.2  2164.7   256.8 2161.83   323.1 2162.25
   375.8 2160.27   422.7 2154.43   440.3 2157.16   455.4 2155.03   473.9 2155.98
   504.7 2154.78   520.1  2156.3   538.5 2154.09     557 2156.04     572 2153.81
   621.4 2157.27   635.6 2160.44   658.7 2172.98   695.6 2197.51   729.2 2216.96
#Mann= 6 ,-1 , 0
       0     .06       0   55.09      .1       0     127    .045       0
   155.1      .1       0  237.87     .05       0  551.66      .1       0
#XS Ineff= 2 , 0
                          179.45         2169.52
Permanent Ineff=
       F       F
Bank Sta=127,155.1
XS Rating Curve= 0 ,0
Exp/Cntr=0.3,0.1

Type RM Length L Ch R = 1 ,14908   ,322.7,334.4,345.1
XS GIS Cut Line= 2
 2454971.5105809542703.7447639252455669.81239257543003.420094164
#Sta/Elev= 30
       0 2180.84    38.4 2168.36    73.2 2160.81      84 2155.81   105.4 2154.57
     121 2151.49   163.2 2149.04   234.2 2150.83     269 2148.38   285.1 2149.36
   295.2 2148.79   312.5 2146.68     330 2147.49   334.3 2148.97   338.7 2151.41
     343 2152.16   373.5 2152.93   399.6 2151.32     416 2152.93   443.4 2153.29
   582.4 2150.56   592.7 2148.53   606.4 2148.08   636.8 2150.31   665.8 2150.52
   677.4 2153.59   696.2 2163.09   708.7 2166.09   734.8  2174.5   759.9 2184.92
#Mann= 6 ,-1 , 0
       0     .05       0   62.42     .06       0  185.78     .05       0
   295.2    .045       0   334.3     .05       0   650.8      .1       0
#XS Ineff= 2 , 0
          229.27 2155.68   368.8         2157.72
Permanent Ineff=
       F       F
Bank Sta=295.2,334.3
XS Rating Curve= 0 ,0
Exp/Cntr=0.3,0.1

Type RM Length L Ch R = 1 ,14573   ,307.8,303.1,296.8
XS GIS Cut Line= 2
2454876.76916448542831.5224890442455442.55705703543465.010110755
#Sta/Elev= 30
       0 2173.64    43.4  2159.9    88.8 2148.01   111.1  2147.5   125.6 2145.49
   162.4 2144.98   201.1 2140.77   208.3 2140.94   225.42137.943   243.2 2137.94
   261.2 2143.93   267.2 2144.47   318.2 2145.87   372.1 2145.88   429.3 2143.16
   495.4  2144.3     525  2142.5   567.4  2142.2   615.9 2139.14   648.1 2138.65
   666.7 2134.25   675.2 2133.72     695 2136.71   733.9 2136.72   744.6 2135.42
   766.1 2137.76   771.6 2139.26   819.7 2159.89   835.8 2163.58   849.4 2165.13
#Mann= 9 ,-1 , 0
       0     .05       0  100.57     .06       0  216.78     .05       0
   225.4    .045       0   243.2     .05       0  332.99      .1       0
   449.2     .05       0  494.22      .1       0  565.41     .05       0
#XS Ineff= 2 , 0
                          290.97         2151.69
Permanent Ineff=
       F       F
Bank Sta=225.4,243.2
XS Rating Curve= 0 ,0
Exp/Cntr=0.3,0.1

Type RM Length L Ch R = 1 ,14270   ,81.5,80.7,80.8
XS GIS Cut Line= 2
2454590.69796061543112.1940939552455339.99885211543491.252192008
#Sta/Elev= 30
       0 2173.77    26.9 2169.96    43.7 2165.82    62.8 2159.87    85.2 2151.02
     133 2136.11     267 2136.78   273.5 2136.02   287.8 2131.85   295.9 2130.88
   309.4  2131.8   318.3 2137.35   323.5 2138.45   385.6 2135.92   461.8 2136.08
   470.7 2136.58   484.5 2140.35   493.2 2140.88   511.1 2139.97     529  2141.3
   540.8 2139.84   596.3 2138.03   603.4 2136.62   623.1 2130.22   639.1 2128.91
   652.8 2129.27   690.4 2132.96   802.5  2136.3   817.7 2139.13   839.7 2148.23
#Mann= 8 ,-1 , 0
       0      .1       0  119.58     .06       0   246.2      .1       0
   287.8    .045       0   309.4      .1       0  488.08     .05       0
  580.76      .1       0  610.91     .05       0
#XS Ineff= 2 , 0
                          331.29         2143.83
Permanent Ineff=
       F       F
Bank Sta=287.8,309.4
XS Rating Curve= 0 ,0
Exp/Cntr(USF)=0,0
Exp/Cntr=0.5,0.3

Type RM Length L Ch R = 1 ,14189   ,58.6,58.4,57.7
XS GIS Cut Line= 3
2454475.13671854543161.2923321272455111.12036191543447.682081753
 2455308.6188348543544.042166822
#Sta/Elev= 30
       0 2176.81    21.5 2175.08    39.1 2171.31    55.4 2170.37    74.1 2164.81
   100.7 2151.26   113.6 2146.44   161.9  2137.8   201.4 2134.37   336.7 2134.87
   345.7 2133.87   354.6 2129.48     373 2129.72   385.6 2135.26   442.5 2137.89
   457.7 2136.81   482.1 2138.19   504.1    2136     526 2136.14   578.6 2133.53
     618 2136.24   637.1 2133.63   653.2 2127.01     662 2126.34   690.3 2131.53
   759.5    2131   843.2 2133.96   864.1  2136.4   897.4 2138.36   917.2 2142.31
#Mann= 6 ,-1 , 0
       0      .1       0  262.03     .06       0   354.6    .045       0
     373     .06       0  381.06      .1       0  739.04     .05       0
#XS Ineff= 2 , 0
          341.81  2134.5  383.87          2134.5
Permanent Ineff=
       F       F
Bank Sta=354.6,373
XS Rating Curve= 0 ,0
Exp/Cntr=0.5,0.3

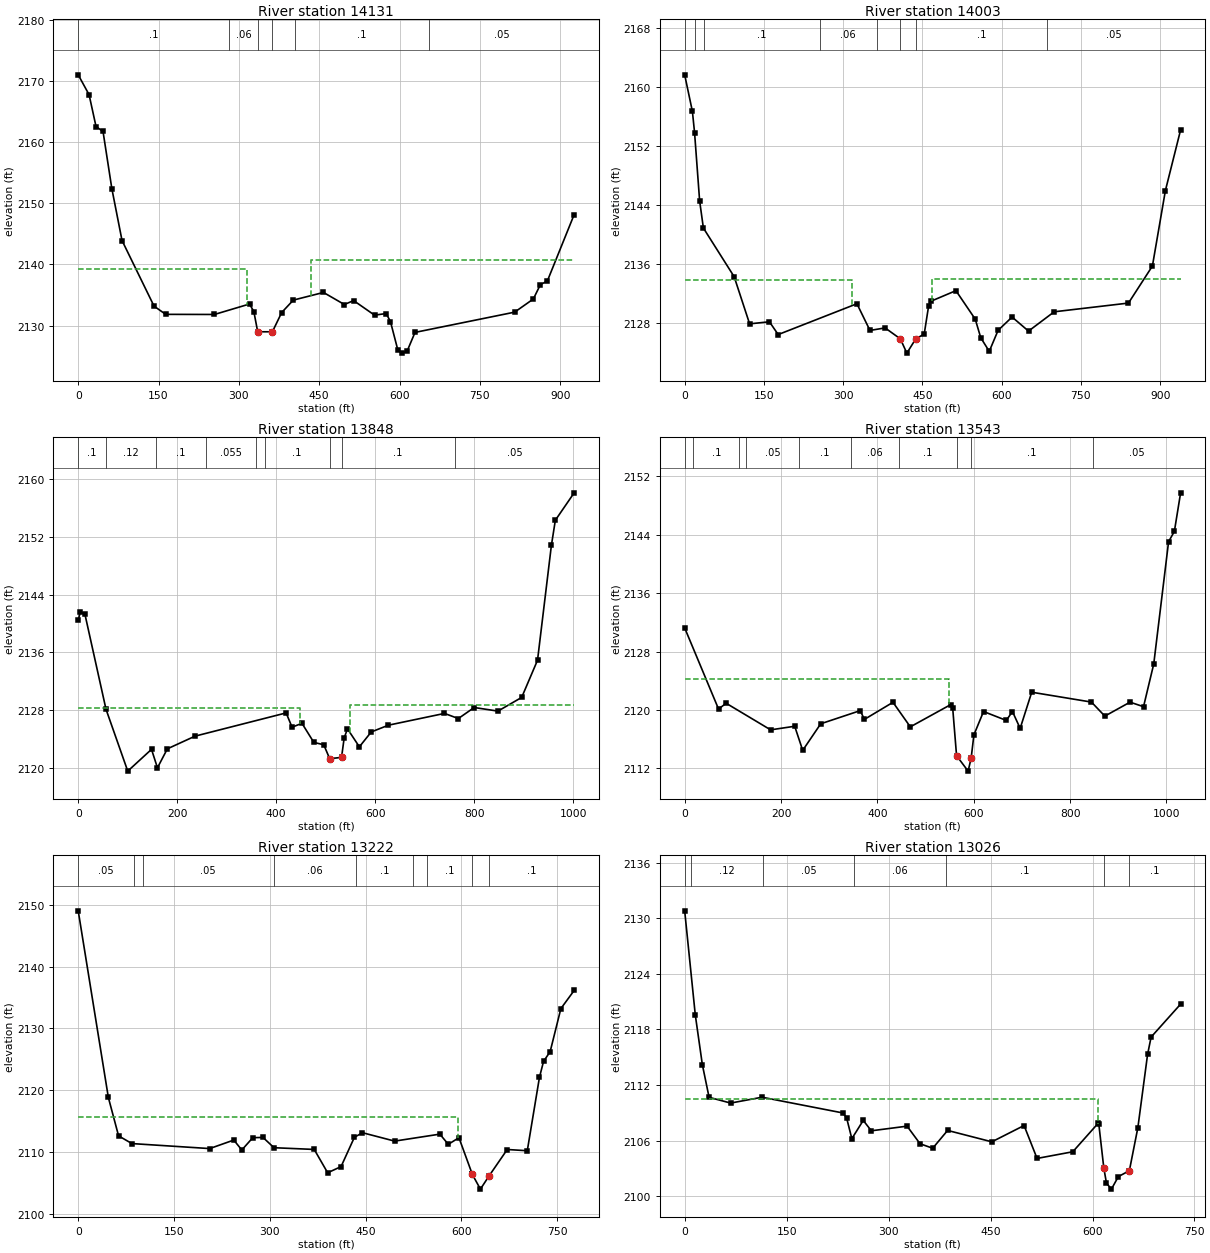
Type RM Length L Ch R = 1 ,14131   ,132.4,128.2,127.5
XS GIS Cut Line= 3
2454460.01912945543227.4475045992455041.86040005543469.756490438
2455312.49591214543588.764101685
#Sta/Elev= 30
       0    2171    20.3 2167.75    33.3 2162.53    46.3 2161.75    62.8 2152.39
    81.8 2143.91   141.6 2133.18   163.3 2131.84   254.3 2131.82   319.8 2133.53
   327.9  2132.3   335.1 2128.99   362.5 2128.99   379.9 2132.14   401.6 2134.17
   457.9 2135.42   496.9 2133.45   514.2 2134.09   553.2 2131.71   574.9 2131.97
   582.9 2130.67   596.6 2126.05   604.3  2125.5   613.9 2125.79   628.8 2128.89
   814.8  2132.2   849.7 2134.35   862.8 2136.69   875.9  2137.3   925.9 2148.15
#Mann= 6 ,-1 , 0
       0      .1       0  282.28     .06       0   335.1    .045       0
   362.5     .06       0  404.19      .1       0  655.45     .05       0
#XS Ineff= 2 , 0
          315.51 2139.22  433.83         2140.65
Permanent Ineff=
       F       F
Bank Sta=335.1,362.5
XS Rating Curve= 0 ,0
Exp/Cntr=0.5,0.3

Type RM Length L Ch R = 1 ,14003   ,160.8,155.1,149.9
XS GIS Cut Line= 3
2454396.76125928543377.7551452072454634.57018896543446.871871543
2455306.80173726543607.157359644
#Sta/Elev= 30
       0 2161.63    14.6 2156.69    18.7 2153.82    28.3 2144.58    35.4 2140.91
    93.7 2134.32   122.9 2127.95   160.4 2128.23     177  2126.5     326 2130.67
   350.7 2127.06   379.4  2127.4   408.2 2125.92   420.5 2123.99   437.1 2125.89
   453.4 2126.58   461.7 2130.36   465.8    2131   513.4 2132.44     550 2128.58
   560.4 2126.07   576.5 2124.23   593.2 2127.07   619.7 2128.87   650.8 2126.97
   699.4 2129.58     840 2130.76   885.3 2135.77   909.9 2145.98   938.7 2154.19
#Mann= 8 ,-1 , 0
       0      .1       0   19.88     .12       0   36.18      .1       0
  255.92     .06       0  363.51      .1       0   408.2    .045       0
   437.1      .1       0   686.3     .05       0
#XS Ineff= 2 , 0
          317.27 2133.85  468.89         2133.95
Permanent Ineff=
       F       F
Bank Sta=408.2,437.1
XS Rating Curve= 0 ,0
Exp/Cntr(USF)=0,0
Exp/Cntr=0.3,0.1

Type RM Length L Ch R = 1 ,13848   ,303.6,304.2,296.7
XS GIS Cut Line= 2
2454314.67839336543637.4561754442455316.78823438 543635.20460746
#Sta/Elev= 30
       0 2140.44     4.1 2141.59    13.5 2141.31    56.1 2128.13   100.1 2119.54
   148.1 2122.56   160.1    2120   180.1 2122.63   236.1 2124.39   420.1 2127.61
   432.1 2125.63   452.1 2126.17   476.1 2123.52   496.1  2123.2   508.1 2121.27
   532.1 2121.44   537.4 2124.15   544.1  2125.4   568.1 2122.91   592.1 2124.97
   626.9 2125.91   740.1 2127.54   768.1 2126.83   800.1 2128.36   848.1 2127.86
   896.1 2129.76   928.1 2134.92   956.1 2150.83   964.1 2154.32  1002.1 2158.12
#Mann= 9 ,-1 , 0
       0      .1       0   56.66     .12       0  157.24      .1       0
  257.82    .055       0   358.4     .06       0  376.61      .1       0
   508.1    .045       0   532.1      .1       0  760.71     .05       0
#XS Ineff= 2 , 0
          448.03 2128.33  548.99         2128.64
Permanent Ineff=
       F       F
Bank Sta=508.1,532.1
XS Rating Curve= 0 ,0
Exp/Cntr=0.3,0.1

Type RM Length L Ch R = 1 ,13543   ,314.2,320.8,325.7
XS GIS Cut Line= 3
2454175.14783442543767.275725863 2454495.8038059543858.778513157
2455191.80210855543848.883564683
#Sta/Elev= 30
       0 2131.23    70.3 2120.13    86.1 2120.92   178.4 2117.28   228.4 2117.77
     245 2114.47   282.4 2118.11   364.4 2119.91   373.1 2118.71   432.4 2121.05
   468.4 2117.69   552.4 2120.74   556.4 2120.23   564.4 2113.74   588.4 2111.63
   594.72113.432   600.4 2116.59   620.4 2119.79   667.6 2118.57   680.4 2119.79
   696.4 2117.48   720.4 2122.43   844.4 2121.08   872.2 2119.16   924.5 2121.07
   952.5 2120.45   973.7 2126.29  1004.5 2143.03  1016.5 2144.44  1029.5 2149.72
#Mann= 10 ,-1 , 0
       0     .05       0   17.48      .1       0  113.73     .12       0
  127.19     .05       0   236.9      .1       0  345.49     .06       0
  445.88      .1       0   564.4    .045       0   594.7      .1       0
  847.46     .05       0
#XS Ineff= 2 , 0
          548.99 2124.26
Permanent Ineff=
       F       F
Bank Sta=564.4,594.7
XS Rating Curve= 0 ,0
Exp/Cntr=0.3,0.1

Type RM Length L Ch R = 1 ,13222   ,191.1,196.4,204
XS GIS Cut Line= 2
2454134.56994187543979.7177280642454874.59372476544215.198268635
#Sta/Elev= 30
       0 2149.06    47.2 2118.82    63.2  2112.6    84.1 2111.35   205.9 2110.54
   243.6 2111.92   256.2 2110.31   273.3  2112.3   289.3 2112.35   306.6 2110.68
   369.6  2110.4   390.6 2106.62   411.6 2107.62   432.5 2112.37   445.1 2113.11
   495.5 2111.75   566.3 2112.88   579.5 2111.23   596.2  2112.3   617.2 2106.35
   617.2 2106.34   629.8 2103.97   643.7 2106.16   671.8 2110.39   703.2 2110.19
   722.3  2122.1   728.7 2124.67     739 2126.24   755.8 2133.22   776.6 2136.16
#Mann= 9 ,-1 , 0
       0     .05       0   87.41     .12       0  100.76     .05       0
  306.14     .06       0  434.75      .1       0  524.87      .1       0
  546.08      .1       0   617.2    .045       0   643.7      .1       0
#XS Ineff= 2 , 0
          595.27 2115.68
Permanent Ineff=
       F       F
Bank Sta=617.2,643.7
XS Rating Curve= 0 ,0
Exp/Cntr=0.3,0.1

Type RM Length L Ch R = 1 ,13026   ,101.7,104.9,106.8
XS GIS Cut Line= 2
2454144.98029385544011.0172949482454755.39524452544410.628055928
#Sta/Elev= 30
       0 2130.79    15.6 2119.57      26  2114.2    35.9 2110.68    67.6 2110.06
   113.9 2110.69   232.3    2109   238.1  2108.5   245.9 2106.22   262.7 2108.19
   274.6 2107.07   327.2 2107.57   346.3 2105.67   364.9 2105.19   386.8 2107.11
   451.9 2105.88   499.3 2107.64   518.4 2104.09     571 2104.81     608 2107.86
   609.3 2107.76   616.6 2103.06   620.5 2101.43   627.8 2100.78     638 2102.13
   654.2 2102.77   666.7 2107.41     681 2115.31   686.2 2117.18   729.6 2120.73
#Mann= 7 ,-1 , 0
       0     .05       0    9.63     .12       0  114.63     .05       0
  249.17     .06       0  383.71      .1       0   616.6    .045       0
   654.2      .1       0
#XS Ineff= 2 , 0
          607.89 2110.55
Permanent Ineff=
       F       F
Bank Sta=616.6,654.2
XS Rating Curve= 0 ,0
Exp/Cntr=0.5,0.3