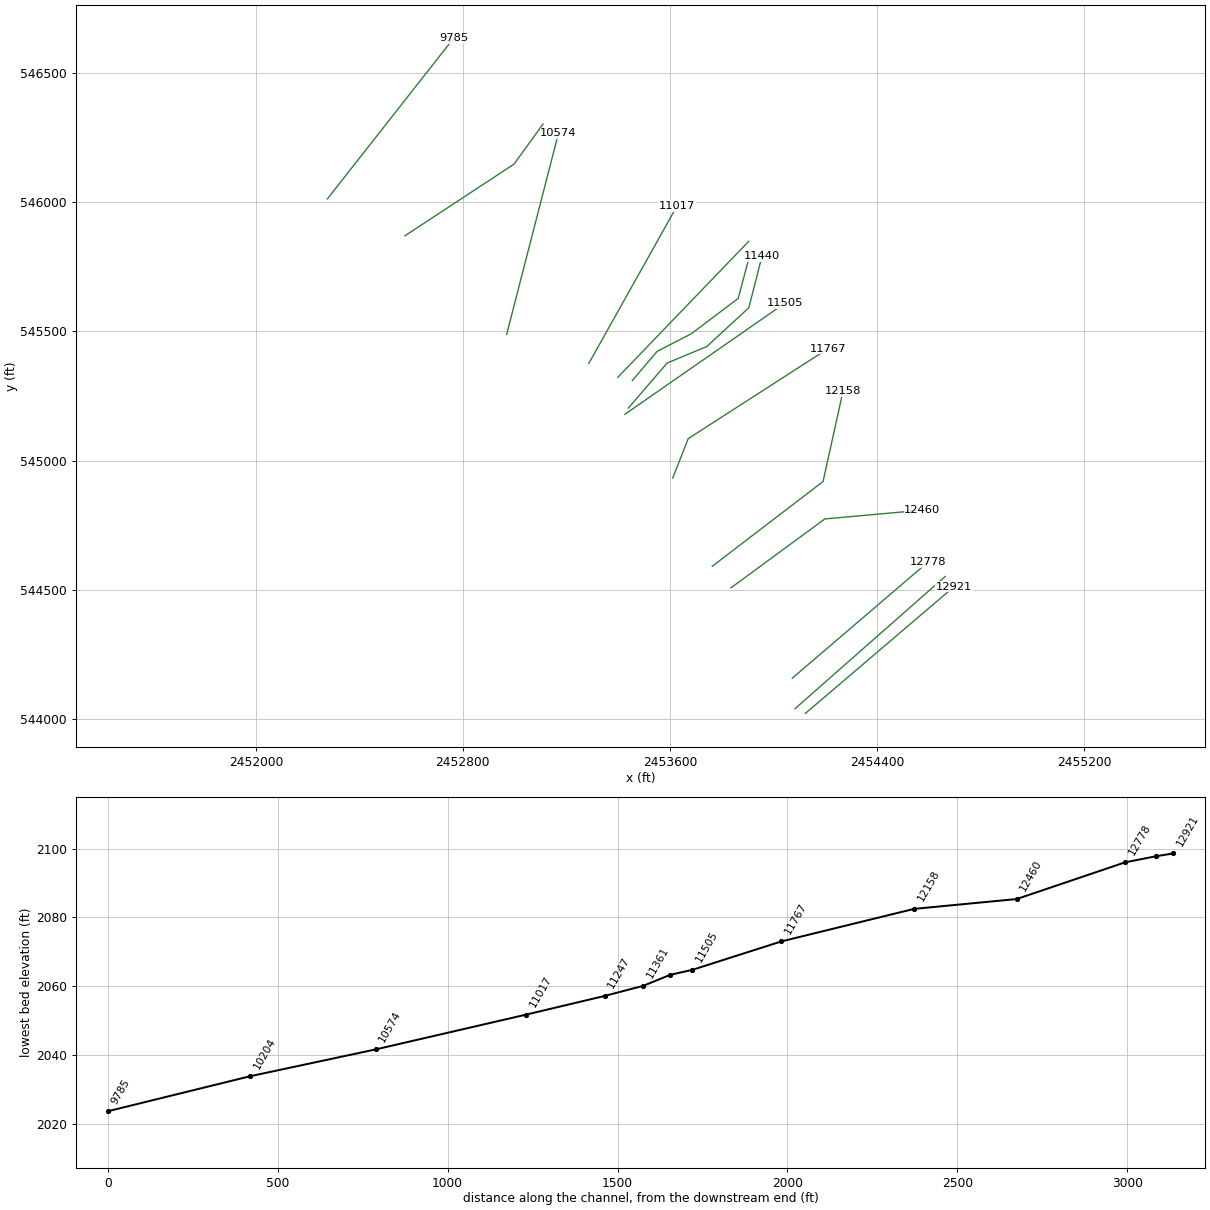
HEC-RAS study STONYRN.prj: STONYRN

--- STONYRN.g01 (geometry) --- (continued)

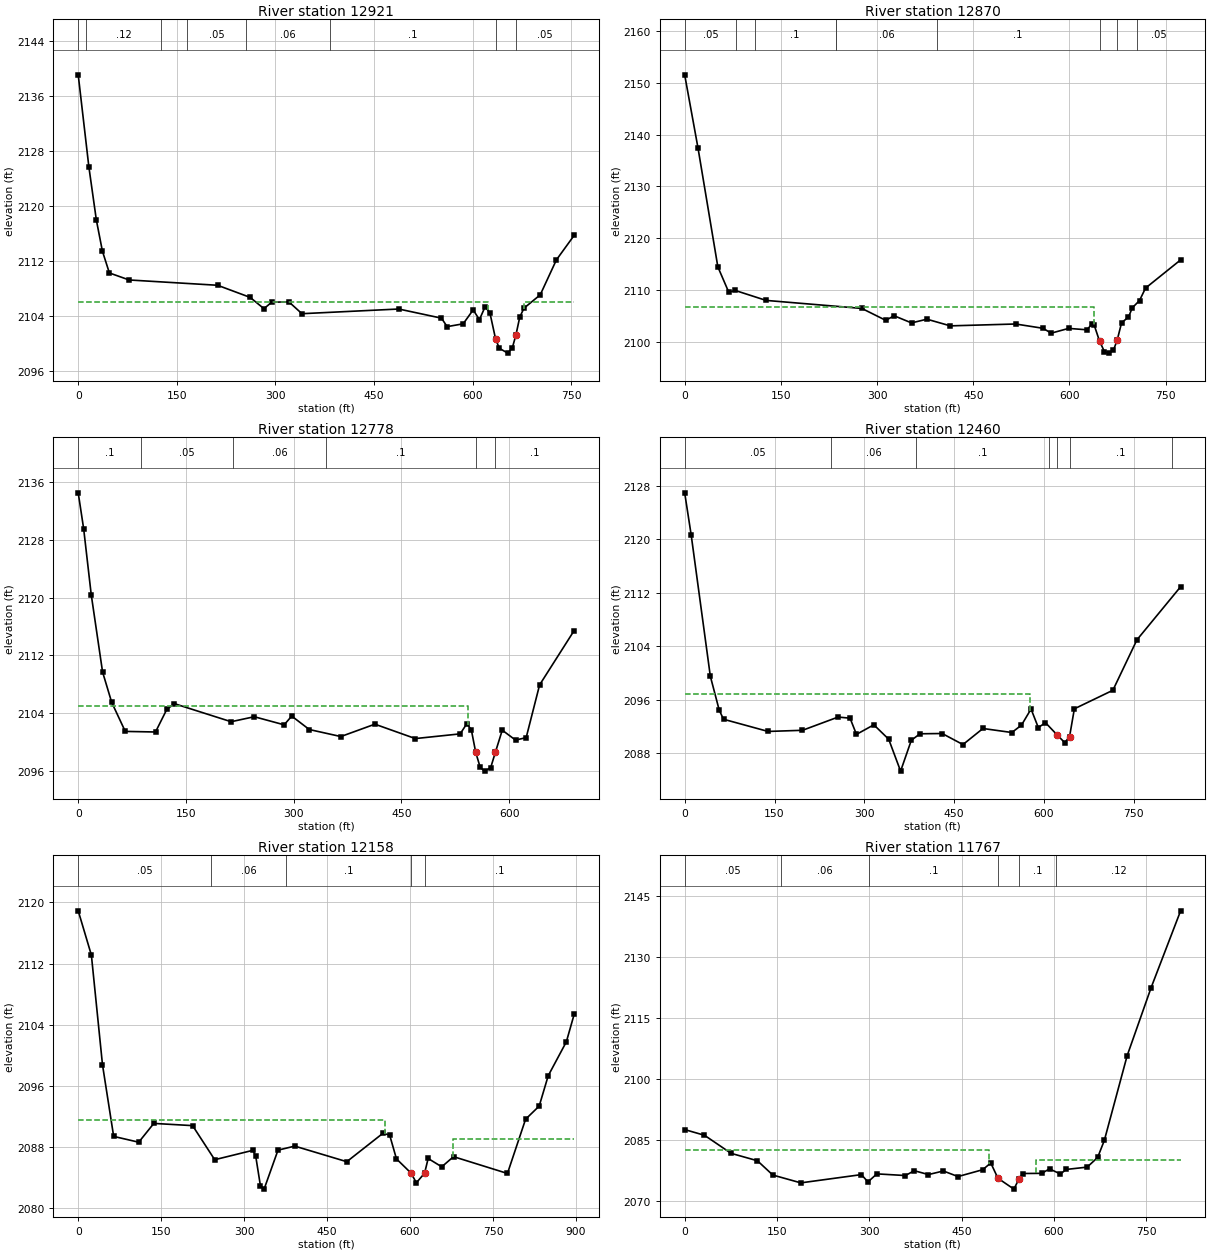
Type RM Length L Ch R = 1 ,12921   ,50.8,51.3,51.9
XS GIS Cut Line= 2
2454123.77483442544023.0131052532454697.75801968544512.386358467
#Sta/Elev= 30
       0 2139.05    16.2 2125.68    27.6 2117.95    36.8 2113.43    47.4 2110.26
    77.5 2109.24     212 2108.47   261.5 2106.71   282.5 2105.07   294.3 2106.01
   320.4 2106.06   340.3 2104.34   487.5 2105.02   552.5 2103.69   561.1 2102.46
   585.5 2102.87   600.7 2104.89   610.2 2103.48   618.9 2105.35   626.2 2104.45
   634.7 2100.71   640.4 2099.32   653.3 2098.61   660.3 2099.39   665.7 2101.23
   671.6 2103.86     678 2105.14   702.7 2107.08   727.3 2112.16   754.3 2115.72
#Mann= 8 ,-1 , 0
       0     .05       0    12.6     .12       0  125.85      .1       0
  166.03     .05       0  254.53     .06       0  383.21      .1       0
   634.7    .045       0   665.7     .05       0
#XS Ineff= 2 , 0
          622.61    2106   677.3            2106
Permanent Ineff=
       F       F
Bank Sta=634.7,665.7
XS Rating Curve= 0 ,0
Exp/Cntr=0.5,0.3

Type RM Length L Ch R = 1 ,12870   ,90.9,91.5,90.3
XS GIS Cut Line= 2
2454083.53413157544041.0877806912454663.76286924544552.246101896
#Sta/Elev= 30
       0 2151.58    20.9 2137.35    51.7 2114.47    68.7 2109.57    78.9  2109.9
   126.9 2107.98   276.2 2106.43   313.5 2104.13   326.6 2105.01   353.7 2103.63
   377.7 2104.35   414.2 2103.06     516 2103.42   558.7 2102.59   571.5 2101.65
   598.7 2102.57   627.1  2102.3   635.6 2103.47   638.4 2103.26   646.9  2100.1
   654.6 2098.06   661.1 2097.79   668.4  2098.3   674.4 2100.31   681.3 2103.68
     692 2104.75   697.9 2106.54   709.2 2107.96   718.6 2110.36   773.3 2115.81
#Mann= 9 ,-1 , 0
       0     .05       0   79.97     .12       0  108.92      .1       0
  235.85     .05       0   236.4     .06       0  392.84      .1       0
   646.9    .045       0   674.4      .1       0  705.71     .05       0
#XS Ineff= 2 , 0
          637.78 2106.69
Permanent Ineff=
       F       F
Bank Sta=646.9,674.4
XS Rating Curve= 0 ,0
Exp/Cntr=0.5,0.3

Type RM Length L Ch R = 1 ,12778   ,328.9,318.6,308.6
XS GIS Cut Line= 2
 2454072.9628945544159.0189904872454597.46747239 544607.94653986
#Sta/Elev= 30
       0 2134.47     7.6 2129.49    18.1 2120.41    33.9 2109.71    46.6 2105.51
    65.5 2101.49   107.6 2101.41   123.4 2104.55     134 2105.32   212.9 2102.83
   245.1 2103.52   286.7  2102.4   297.2 2103.61   321.7 2101.75   365.6 2100.78
     413 2102.49   469.3  2100.5   531.7 2101.15   541.1 2102.57   547.3 2101.69
   553.4 2098.58   559.6 2096.52   565.7    2096   574.2 2096.48   580.92098.656
   590.3 2101.66   608.8 2100.29   623.6 2100.63   642.3 2107.92   690.4 2115.43
#Mann= 6 ,-1 , 0
       0      .1       0   87.34     .05       0  215.81     .06       0
  344.28      .1       0   553.4    .045       0   580.9      .1       0
#XS Ineff= 2 , 0
          542.72 2104.95
Permanent Ineff=
       F       F
Bank Sta=553.4,580.9
XS Rating Curve= 0 ,0
Exp/Cntr(USF)=0,0
Exp/Cntr=0.3,0.1

Type RM Length L Ch R = 1 ,12460   ,281.9,302.2,323.1
XS GIS Cut Line= 3
2453836.21041611544508.4987845322454198.95020722544774.863453947
2454575.41540953544808.762355258
#Sta/Elev= 30
       0 2126.93    10.8 2120.67    42.8 2099.54    57.7 2094.45    64.9  2093.1
   139.2 2091.28   196.7 2091.45   256.2 2093.43   276.1 2093.26   286.8 2090.84
   315.8 2092.27   340.6 2090.12   360.5 2085.35   378.4 2089.96   392.9 2090.93
   429.9 2090.97   464.6 2089.32     498 2091.72   546.2 2091.12   562.3 2092.22
   578.3 2094.63   590.4 2091.86   602.4 2092.59   621.9 2090.75   634.6  2089.6
   642.6 2090.52   650.6 2094.66   714.9 2097.43   755.1 2104.97     828  2112.9
#Mann= 7 ,-1 , 0
       0     .05       0  244.09     .06       0  385.79      .1       0
  608.59      .1       0   621.9    .045       0   642.6      .1       0
  813.63     .05       0
#XS Ineff= 2 , 0
          576.59 2096.85
Permanent Ineff=
       F       F
Bank Sta=621.9,642.6
XS Rating Curve= 0 ,0
Exp/Cntr=0.3,0.1

Type RM Length L Ch R = 1 ,12158   ,399.8,390.4,372.9
XS GIS Cut Line= 3
2453763.85429933544591.8231957182454191.94891614544919.375793564
2454269.00298025545268.617036178
#Sta/Elev= 30
       0 2118.91    23.8 2113.12    43.9 2098.76    64.1 2089.39   109.4 2088.63
   136.7 2091.09   206.8  2090.8   246.8 2086.34   315.9 2087.57     321 2086.78
   329.5 2082.91   336.1 2082.49   361.2 2087.59   391.5 2088.12   485.6 2086.08
   550.8 2089.79   563.1 2089.57   575.4 2086.45   601.82084.587   611.4 2083.32
   626.3 2084.58   632.7  2086.5   657.3 2085.41   678.6 2086.74   776.1 2084.54
   808.9 2091.64   833.5 2093.36   849.8 2097.33   882.6 2101.77   896.7 2105.36
#Mann= 5 ,-1 , 0
       0     .05       0  240.47     .06       0  375.48      .1       0
   601.8    .045       0   626.3      .1       0
#XS Ineff= 2 , 0
          554.22 2091.54  678.12         2089.04
Permanent Ineff=
       F       F
Bank Sta=601.8,626.3
XS Rating Curve= 0 ,0
Exp/Cntr=0.3,0.1

Type RM Length L Ch R = 1 ,11767   ,263.4,262.4,263.9
XS GIS Cut Line= 3
2453611.03108552544932.8703305862453670.92088156545085.342948181
2454210.99044078545433.136128284
#Sta/Elev= 30
       0 2087.68    32.2 2086.28    75.4 2081.84   118.2 2080.02   143.3  2076.5
   188.8 2074.58   287.3 2076.61   297.9 2074.81   312.4 2076.79   358.8 2076.38
   373.2 2077.57   396.3 2076.62   420.5  2077.5   444.3 2076.13   484.4 2077.81
   497.6 2079.47   509.2 2075.72   535.2 2073.04   543.5 2075.57   549.7 2076.88
   580.4 2076.92   593.1 2078.02   610.8 2076.76   620.3 2077.88   654.3 2078.45
   671.3 2080.82   682.2 2085.02   719.3 2105.85   758.3  2122.6   806.2 2141.46
#Mann= 6 ,-1 , 0
       0     .05       0  156.51     .06       0  299.94      .1       0
   509.2    .045       0   543.5      .1       0  604.12     .12       0
#XS Ineff= 2 , 0
          494.85 2082.59  570.38         2080.15
Permanent Ineff=
       F       F
Bank Sta=509.2,543.5
XS Rating Curve= 0 ,0
Exp/Cntr=0.3,0.1

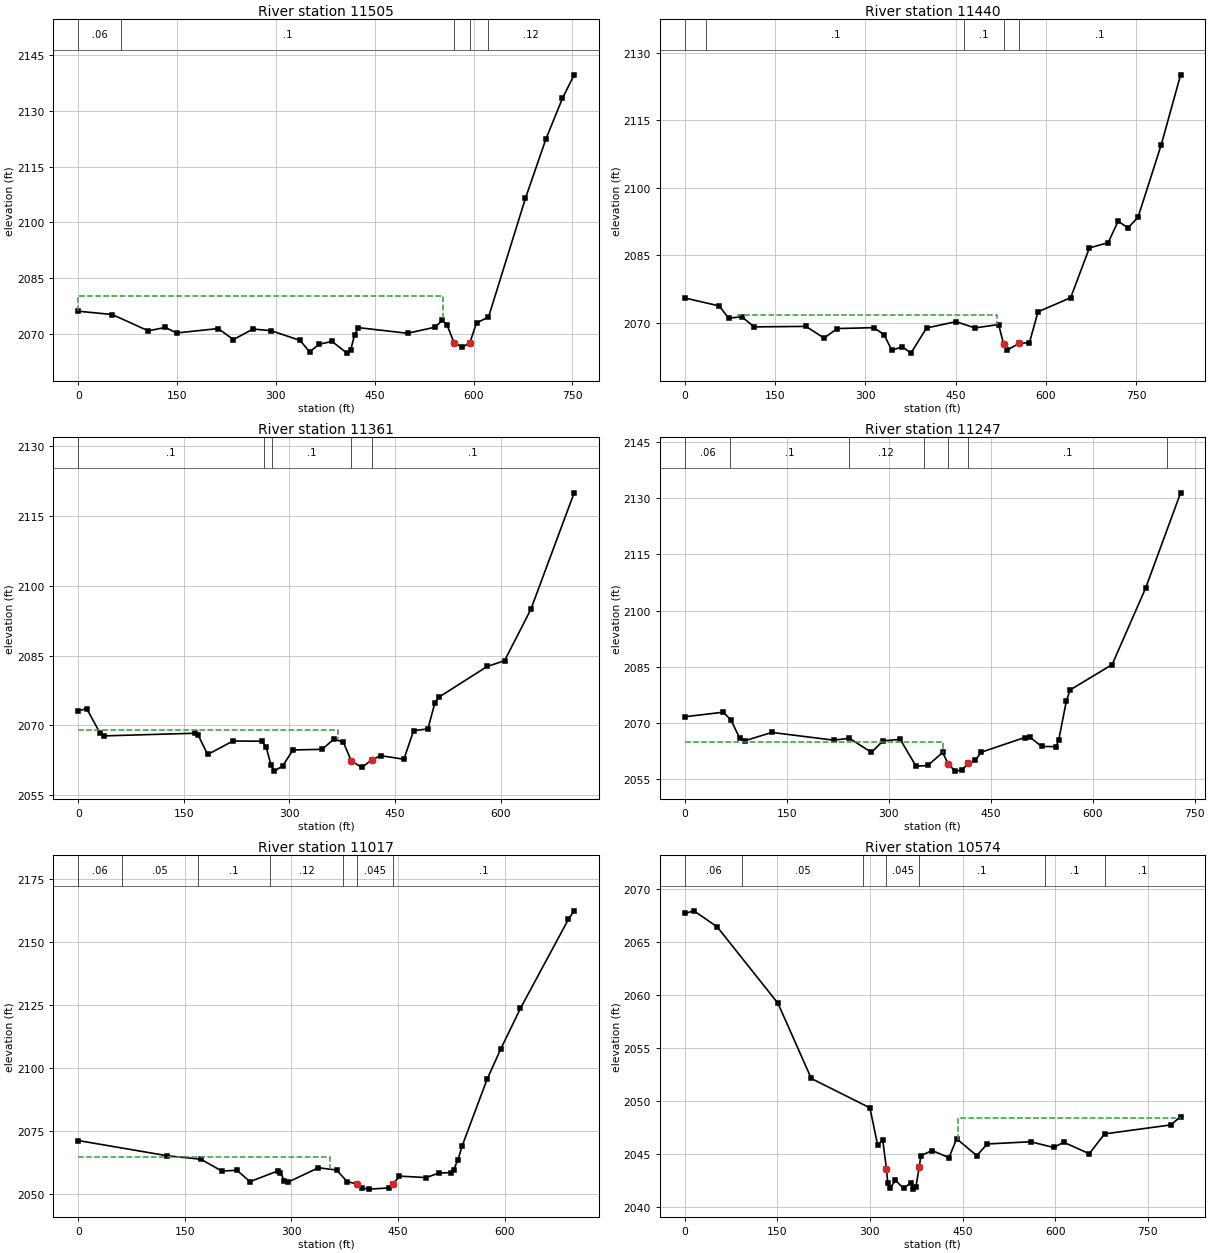
Type RM Length L Ch R = 1 ,11505   ,61.1,64.6,64.2
XS GIS Cut Line= 2
2453426.35492021545179.4923574252454044.40139491545609.050944188
#Sta/Elev= 30
       0 2076.07    51.6 2075.18   106.2 2070.78   132.1 2071.69   149.3 2070.21
   212.5 2071.39   235.5 2068.42   265.3 2071.26   292.7 2070.82   336.6 2068.21
   351.2 2065.12   365.8 2067.19   385.3 2067.91   407.9 2064.77   413.7 2065.74
   419.4 2069.62   425.2 2071.64   499.9 2070.12   541.2 2071.75   552.6 2073.59
   559.6 2072.44   570.62067.514   583.2 2066.37   594.52067.617   604.5 2072.91
   622.7 2074.48   678.8 2106.51   709.7 2122.41   734.9 2133.43   752.7 2139.78
#Mann= 5 ,-1 , 0
       0     .06       0   65.12      .1       0   570.6    .045       0
   594.5      .1       0   622.7     .12       0
#XS Ineff= 2 , 0
          552.94 2080.16
Permanent Ineff=
       F       F
Bank Sta=570.6,594.5
XS Rating Curve= 0 ,0
Exp/Cntr(USF)=0,0
Exp/Cntr=0.5,0.3

Type RM Length L Ch R = 1 ,11440   ,87.6,79.6,80.9
XS GIS Cut Line= 5
2453439.38270474545203.3093030782453589.30853985545377.458236748
2453742.47445738 545441.36919514 2453905.2569153545591.634175332
2453956.10903455545791.515622219
#Sta/Elev= 30
       0 2075.58    57.5  2073.8      73 2071.07    94.5 2071.43   115.5 2069.16
   201.3 2069.27   231.4 2066.69   253.4 2068.79   313.7 2068.99     331 2067.45
     344 2063.96   361.4 2064.76   375.7 2063.34   401.6 2068.91   450.6 2070.32
   481.9 2068.93   521.3 2069.68   529.62065.305   535.7 2064.05   555.5  2065.5
   572.5 2065.68   586.7  2072.5   640.9 2075.63     672 2086.66   703.2 2087.84
   719.7  2092.6   736.2 2091.11   752.8 2093.48   791.4 2109.59   823.5 2125.06
#Mann= 5 ,-1 , 0
       0     .06       0   35.79      .1       0   464.4      .1       0
   529.6    .045       0   555.5      .1       0
#XS Ineff= 1 ,-1
   88.52   518.42071.797
Permanent Ineff=
       F
Bank Sta=529.6,555.5
XS Rating Curve= 0 ,0
Exp/Cntr=0.5,0.3

Type RM Length L Ch R = 1 ,11361   ,105.8,113.5,116.5
XS GIS Cut Line= 5
2453454.88213224545310.006347697 2453550.7415822545422.636672853
2453682.97115129545490.9552835482453864.11035289545627.517218424
2453910.51895621545802.436688979
#Sta/Elev= 30
       0  2073.1    12.1 2073.56    30.6 2068.42    36.8 2067.71   165.9 2068.28
   170.4 2067.88   183.9 2063.71   219.9 2066.61   260.5 2066.56   266.8  2065.4
     274 2061.41   278.7 2060.13   290.6 2061.27   305.1 2064.68   346.5 2064.82
   363.1 2066.99   376.6 2066.39   387.9 2062.34   402.9 2060.92   416.7  2062.5
   429.5 2063.46   462.7 2062.69   476.5 2068.82   496.8 2069.22   506.8 2074.85
   511.9 2075.99     581 2082.64   605.7 2083.87     643  2094.9   704.6 2119.99
#Mann= 5 ,-1 , 0
       0      .1       0  263.38     .12       0   275.6      .1       0
   387.9    .045       0   416.7      .1       0
#XS Ineff= 2 , 0
           368.7 2068.97
Permanent Ineff=
       F       F
Bank Sta=387.9,416.7
XS Rating Curve= 0 ,0
Exp/Cntr=0.5,0.3

Type RM Length L Ch R = 1 ,11247   ,226.1,230.3,236.3
XS GIS Cut Line= 2
2453398.79052384545322.443353189 2453904.5686256545848.055890315
#Sta/Elev= 30
       0  2071.7    56.9 2072.92    68.2  2070.8    80.7 2066.04    89.4 2065.36
   128.3 2067.52   219.2 2065.46   242.2 2065.97   274.7  2062.2   291.7 2065.28
     317 2065.68   340.3  2058.5   357.6 2058.71   379.4 2062.18   387.9 2058.99
     398  2057.2   407.7 2057.47     417 2059.28   427.5 2060.08   435.9 2062.23
   500.2 2066.17   507.6 2066.28   524.9  2063.8   546.3 2063.71   550.2 2065.58
   561.3 2075.85   566.8 2078.85   628.7 2085.63   677.9 2106.01   729.4 2131.44
#Mann= 7 ,-1 , 0
       0     .06       0   66.63      .1       0  241.15     .12       0
  351.85      .1       0   387.9    .045       0     417      .1       0
  709.33      .1       0
#XS Ineff= 2 , 0
          379.62 2065.04
Permanent Ineff=
       F       F
Bank Sta=387.9,417
XS Rating Curve= 0 ,0
Exp/Cntr(USF)=0,0
Exp/Cntr=0.3,0.1

Type RM Length L Ch R = 1 ,11017   ,437.7,443.3,453
XS GIS Cut Line= 2
     2453286.701      545376.0212453627.68926506545984.875987983
#Sta/Elev= 30
       0 2071.09   125.6 2065.03   172.6 2063.67     202 2058.98   223.3 2059.27
   241.7 2054.77   281.3 2059.06   284.3 2058.36   290.1 2055.17   294.8 2054.52
     338 2060.29   363.6 2059.37   378.3  2054.8   392.9 2053.76   398.9 2052.13
   409.4 2051.79   437.1 2052.26   443.4 2053.83   451.8 2056.96   489.3 2056.38
   507.6 2058.16     524 2058.37   528.2 2059.49   534.1 2063.27   540.4 2069.09
   575.2 2095.36   594.7 2107.57   622.2 2123.57   689.8 2159.01   697.8 2162.34
#Mann= 7 ,-1 , 0
       0     .06       0   61.02     .05       0  168.74      .1       0
  269.15     .12       0  373.22      .1       0   392.9    .045       0
   443.4      .1       0
#XS Ineff= 2 , 0
          353.82 2064.45
Permanent Ineff=
       F       F
Bank Sta=392.9,443.4
XS Rating Curve= 0 ,0
Exp/Cntr=0.3,0.1

Type RM Length L Ch R = 1 ,10574   ,393.6,369.4,355.1
XS GIS Cut Line= 2
2452969.25980723545488.3679517962453169.54272288546266.126072284
#Sta/Elev= 30
       0 2067.68      15 2067.93    52.6 2066.42   151.1  2059.2     205 2052.11
     300 2049.34   312.4 2045.84   320.7 2046.31   326.8 2043.56   328.9 2042.23
     333 2041.79   341.3  2042.5   354.7 2041.73   366.1 2042.29   370.2 2041.67
   374.5 2041.89   379.7 2043.73   382.6 2044.84   400.7 2045.31     428 2044.64
   440.4 2046.42     473 2044.83     490 2045.93   560.2 2046.14   597.4  2045.6
   613.9 2046.09   655.2 2045.01   679.9 2046.88   787.4 2047.73   803.1 2048.52
#Mann= 7 ,-1 , 0
       0     .06       0   92.86     .05       0  288.85      .1       0
   326.8    .045       0   379.7      .1       0  582.84      .1       0
  680.84      .1       0
#XS Ineff= 2 , 0
                          442.63         2048.37
Permanent Ineff=
       F       F
Bank Sta=326.8,379.7
XS Rating Curve= 0 ,0
Exp/Cntr=0.3,0.1

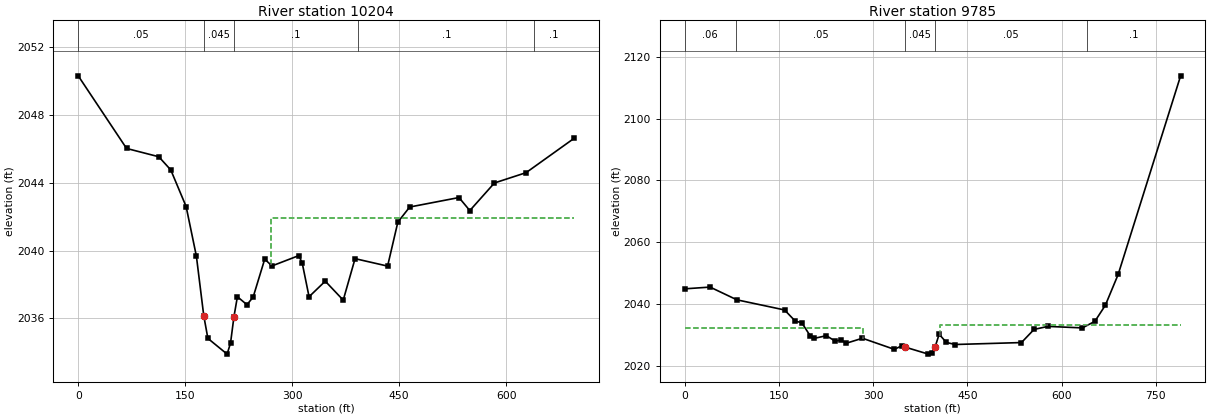
Type RM Length L Ch R = 1 ,10204   ,403.3,419.1,423.7
XS GIS Cut Line= 3
2452576.29044178545869.6147770542452997.85645424546146.817936071
2453109.69464377546301.490363793
#Sta/Elev= 30
       0 2050.32    67.8 2046.03     113 2045.54   129.8 2044.76   151.3  2042.6
   165.7 2039.67     176 2036.16   181.8 2034.81   208.8 2033.88   213.6 2034.54
   218.4  2036.1   223.2 2037.27   236.6  2036.8   245.3 2037.25   261.5 2039.49
   271.7 2039.09   309.3  2039.7   314.1 2039.26   323.7 2037.27   346.4 2038.19
   371.6 2037.07   388.2 2039.52   433.8 2039.08   448.2 2041.68   464.8 2042.57
   533.9 2043.13   549.1 2042.36   583.6 2043.99     628  2044.6   695.4 2046.63
#Mann= 5 ,-1 , 0
       0     .05       0     176    .045       0   218.4      .1       0
   392.8      .1       0  639.33      .1       0
#XS Ineff= 2 , 0
                          270.55          2041.9
Permanent Ineff=
       F       F
Bank Sta=176,218.4
XS Rating Curve= 0 ,0
Exp/Cntr=0.3,0.1

Type RM Length L Ch R = 1 ,9785    ,266,287.9,295.9
XS GIS Cut Line= 2
2452276.56713597 546012.40546053     2452764.196      546633.108
#Sta/Elev= 30
       0 2044.86    40.4 2045.43    83.1  2041.3   158.9 2038.02   176.1 2034.38
   186.3  2033.9   199.9 2029.59   205.6 2028.78   225.5 2029.68   239.8 2027.88
   248.3  2028.3   257.5 2027.25   282.9 2028.85   333.7 2025.25   345.2 2026.37
   350.9 2025.97   387.9  2023.7   393.6 2023.99   398.5 2025.99     405 2030.16
   416.4  2027.5   430.4 2026.82     536 2027.45     556  2031.7     578 2032.69
   632.9  2032.2   652.8 2034.32   669.5 2039.53   689.9 2049.53   789.3  2113.9
#Mann= 5 ,-1 , 0
       0     .06       0   81.43     .05       0   350.9    .045       0
   398.5     .05       0  640.74      .1       0
#XS Ineff= 2 , 0
          284.27 2032.25  406.86         2033.18
Permanent Ineff=
       F       F
Bank Sta=350.9,398.5
XS Rating Curve= 0 ,0
Exp/Cntr=0.3,0.1