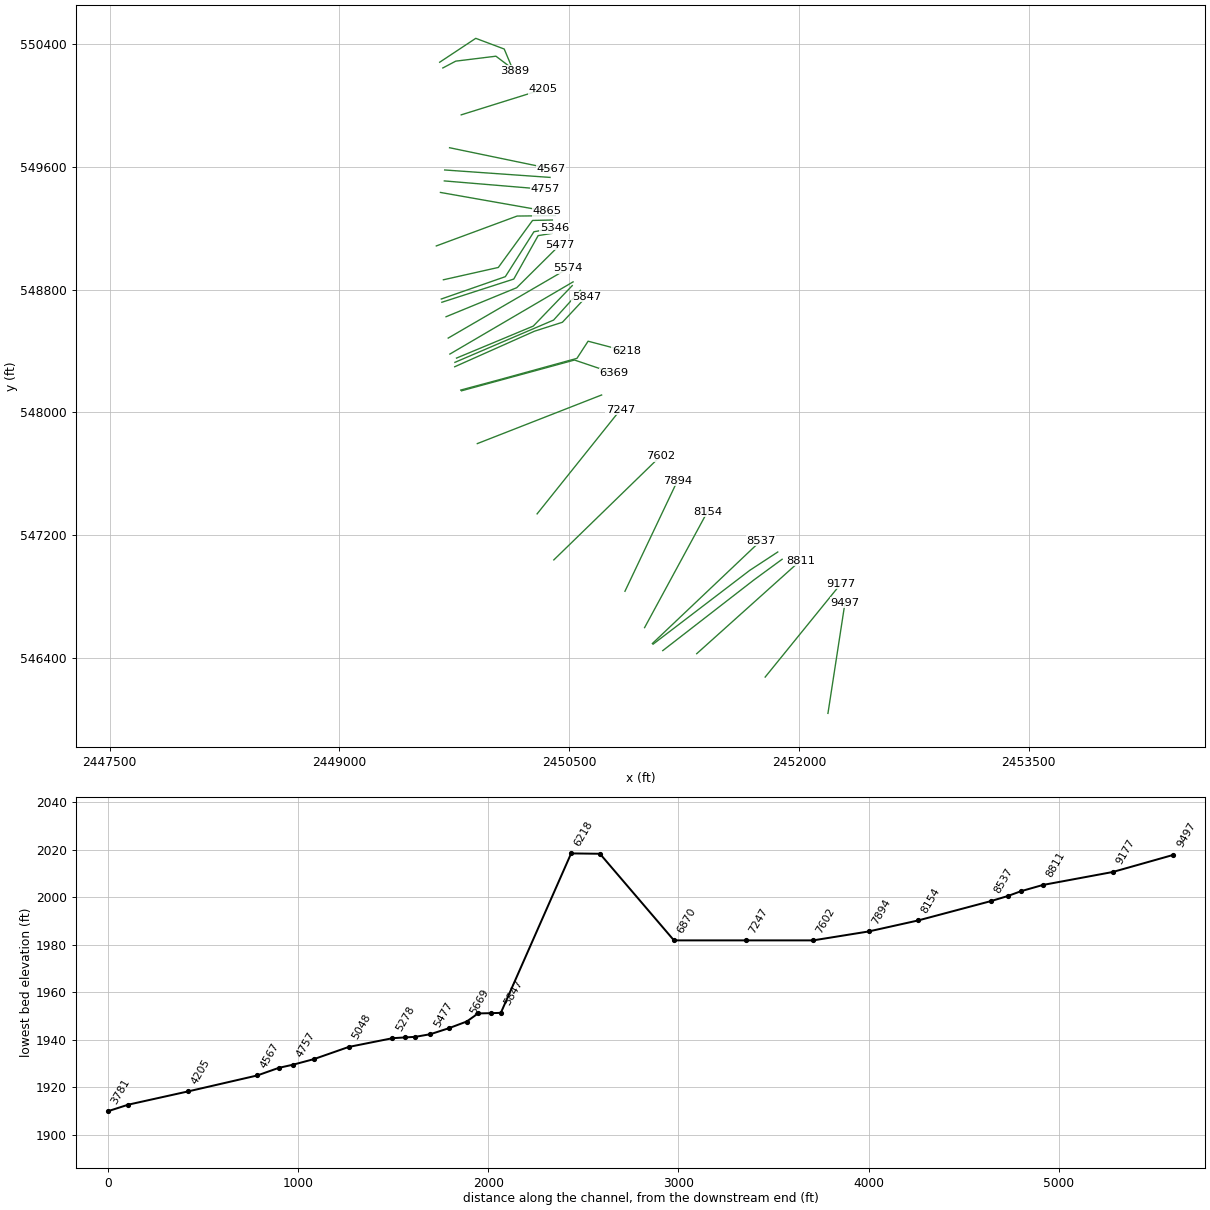
HEC-RAS study STONYRN.prj: STONYRN

--- STONYRN.g01 (geometry) --- (continued)

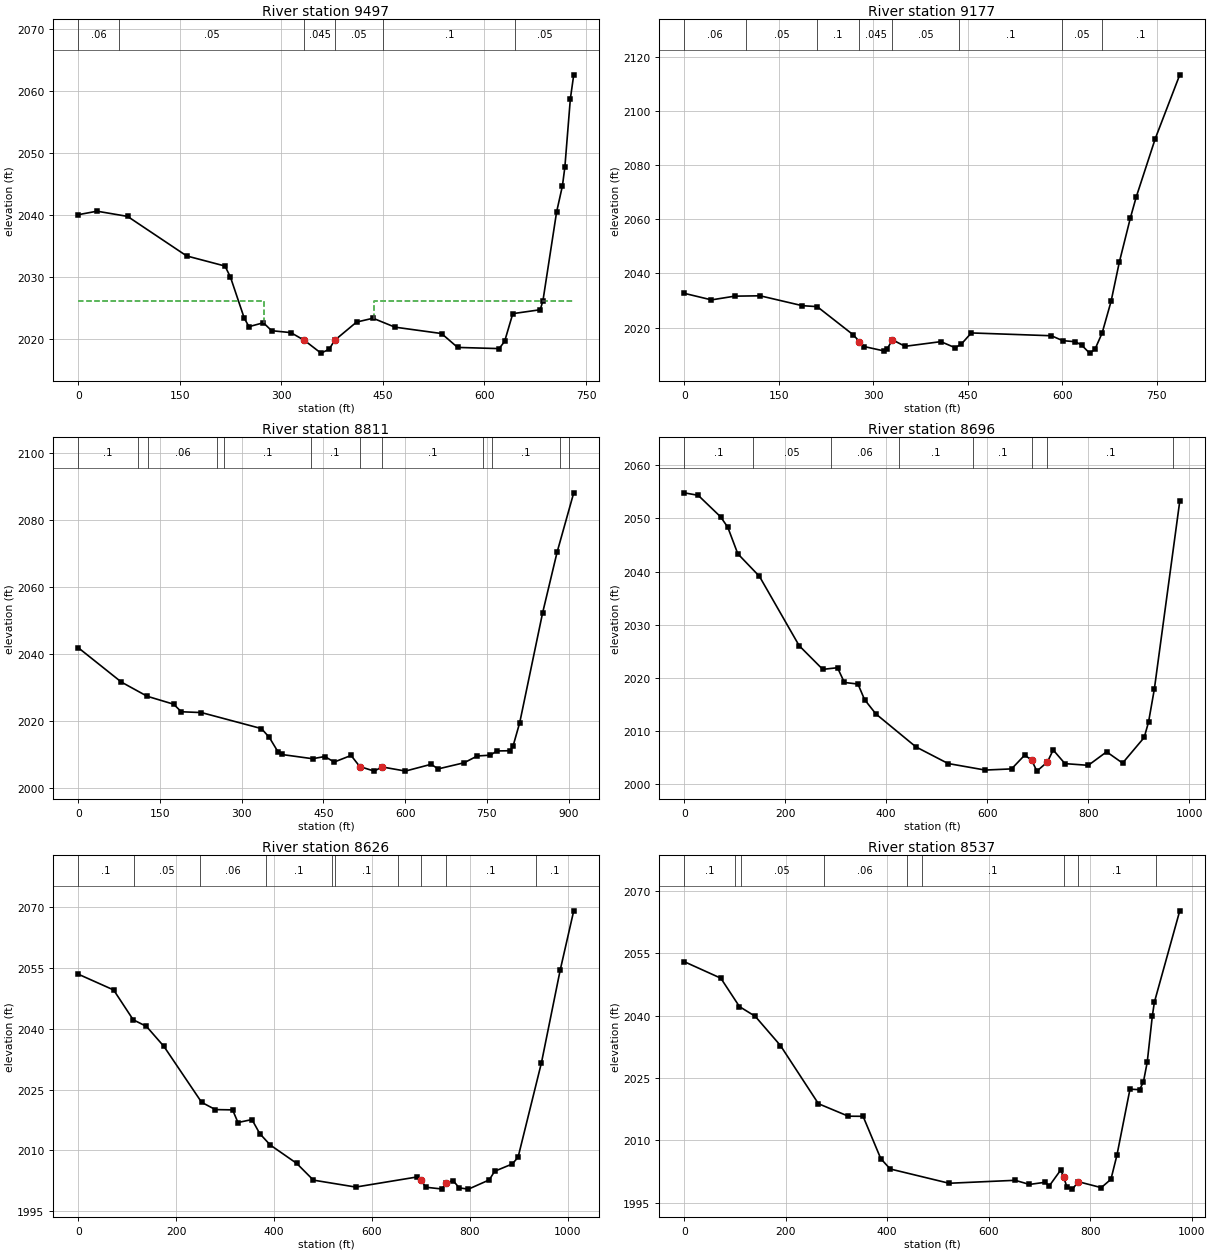
Type RM Length L Ch R = 1 ,9497    ,337.3,319.8,307.8
XS GIS Cut Line= 2
2452189.37897369546036.5894304372452300.86830239546759.831611794
#Sta/Elev= 30
       0 2040.08    27.8 2040.65    72.9 2039.81   160.2 2033.43   216.8  2031.8
   224.9    2030   245.2  2023.4   252.2 2022.02   273.5 2022.65   285.6 2021.37
     314 2021.06   334.2  2019.8   358.5 2017.75   370.6 2018.37   378.7 2019.81
   411.1 2022.76   435.4 2023.38   467.8 2021.94   536.6 2020.91   560.3 2018.67
   621.6 2018.48   629.7 2019.63   641.8 2024.12   682.3 2024.75   686.3 2026.18
   706.5 2040.52   715.1 2044.73   718.7 2047.75   726.8 2058.76   731.8 2062.65
#Mann= 6 ,-1 , 0
       0     .06       0   60.48     .05       0   334.2    .045       0
   378.7     .05       0  450.59      .1       0  645.64     .05       0
#XS Ineff= 2 , 0
          273.86 2026.24  436.93         2026.15
Permanent Ineff=
       F       F
Bank Sta=334.2,378.7
XS Rating Curve= 0 ,0
Exp/Cntr=0.3,0.1

Type RM Length L Ch R = 1 ,9177    ,372.4,366.6,362.9
XS GIS Cut Line= 2
 2451779.3889482546273.3721253232452275.20620523546883.796910822
#Sta/Elev= 30
       0 2032.66    43.2 2030.23    80.2 2031.61   120.5 2031.74   187.5 2028.08
     211 2027.74   267.9 2017.36   278.1 2014.82   285.4 2012.97   316.3 2011.38
   321.5 2011.89   330.5 2015.45   350.4 2013.05   407.3 2014.78     430 2012.52
     440 2013.93   455.6    2018   582.7 2016.96   600.6 2015.15   620.7 2014.75
   630.7  2013.5   643.3 2010.53   651.8 2011.92   663.2 2017.96   677.4 2029.68
   690.5 2044.19     708 2060.52   717.2  2068.2   747.6 2089.93   786.4  2113.5
#Mann= 8 ,-1 , 0
       0     .06       0   97.81     .05       0  210.71      .1       0
   278.1    .045       0   330.5     .05       0  436.53      .1       0
  600.05     .05       0  662.34      .1       0
Bank Sta=278.1,330.5
XS Rating Curve= 0 ,0
Exp/Cntr=0.3,0.1

Type RM Length L Ch R = 1 ,8811    ,116.9,114.8,113.1
XS GIS Cut Line= 2
2451332.48246324546425.9200070772452009.52745072547033.104845835
#Sta/Elev= 30
       0 2041.88    79.3 2031.62   126.6  2027.4   175.2 2025.03   189.2 2022.78
   226.1 2022.54   336.2 2017.77   350.7 2015.15   366.9 2010.77   373.4 2010.05
     430 2008.79   452.7 2009.44   469.7 2007.79   500.8 2009.76   516.7 2006.46
   543.3 2005.09   557.5 2006.34   600.6 2005.11   647.8 2007.13   660.5 2005.75
   708.4 2007.59   732.4 2009.61   756.3 2009.84   768.3  2011.1   792.9 2011.17
   798.3 2012.69   810.3 2019.55   852.2 2052.19   878.8 2070.28   909.4 2088.02
#Mann= 12 ,-1 , 0
       0      .1       0  110.23     .05       0  129.01     .06       0
  255.02    .055       0  268.38      .1       0  426.53      .1       0
   516.7    .045       0   557.5      .1       0  742.82      .1       0
  759.03      .1       0  885.03     .12       0  900.97      .1       0
Bank Sta=516.7,557.5
XS Rating Curve= 0 ,0
Exp/Cntr=0.5,0.3

Type RM Length L Ch R = 1 ,8696    ,68.8,69.7,67.2
XS GIS Cut Line= 3
2451110.83264143 546445.923505742451706.09669232546907.142956878
2451890.12566776547041.917925984
#Sta/Elev= 30
       0  2054.8    27.7 2054.33    71.9  2050.3    86.2 2048.34   106.1 2043.34
   148.9  2039.1   227.6 2026.06   274.3 2021.61   303.5 2021.92   317.1 2019.15
     344 2018.85     357 2015.94   379.4 2013.24   458.7 2007.04   522.4 2003.91
   595.9 2002.68   648.1  2002.9   674.3 2005.51   688.1  2004.5   698.2 2002.48
   719.1  2004.2   730.5 2006.46   753.8 2003.89     800 2003.57   836.3 2006.11
   867.9 2003.99   910.7 2008.81   919.3  2011.7   930.8  2017.9   981.1 2053.22
#Mann= 8 ,-1 , 0
       0      .1       0   135.7     .05       0  291.29     .06       0
  425.52      .1       0  572.42      .1       0   688.1    .045       0
   719.1      .1       0  968.04      .1       0
#XS Ineff= 2 , 0
          675.72    2004  730.94            2004
Permanent Ineff=
       F       F
Bank Sta=688.1,719.1
XS Rating Curve= 0 ,0
Exp/Cntr=0.5,0.3

Type RM Length L Ch R = 1 ,8626    ,95.7,88.7,91.8
XS GIS Cut Line= 3
2451047.90955344546488.2226554112451679.03632566546969.786053727
2451861.86291666547089.462512057
#Sta/Elev= 30
       0 2053.47    72.4 2049.57   112.4 2042.21   139.4 2040.59   175.2 2035.64
   252.2 2021.85   280.3 2020.06   315.5 2019.99   326.4 2016.87     355  2017.6
   370.9 2014.15   392.1 2011.35   446.3  2006.8   480.5 2002.66   567.1 2000.95
   692.9 2003.45   700.3 2002.76     710 2000.91   743.2 2000.47   751.6 2001.98
   765.9 2002.56   778.4 2000.75   797.3 2000.44   839.7 2002.71   850.9 2004.85
   886.9 2006.65   898.7 2008.31   946.5 2031.65   984.7 2054.45  1012.4 2069.09
#Mann= 10 ,-1 , 0
       0      .1       0  113.62     .05       0   248.8     .06       0
  383.99      .1       0  519.17      .1       0  523.67      .1       0
  654.36      .1       0   700.3    .045       0   751.6      .1       0
  934.86      .1       0
Bank Sta=700.3,751.6
XS Rating Curve= 0 ,0
Exp/Cntr=0.5,0.3

Type RM Length L Ch R = 1 ,8537    ,376.8,383.7,386.7
XS GIS Cut Line= 2
2451043.20586526546492.4909442762451752.17796254547164.125329151
#Sta/Elev= 30
       0 2052.98    72.1 2049.01   108.9 2042.18     140 2039.84   189.6 2032.83
   264.5 2018.84   323.4 2015.84   352.5 2015.81   387.4 2005.63     406 2003.15
     522 1999.72   652.1 2000.43   680.4 1999.44   711.6 1999.96   718.9 1998.99
   742.1 2002.92     748 2001.17     754 1998.87   765.2 1998.31   776.6  2000.1
   821.9 1998.67     841 2000.68   852.7 2006.42   878.5 2022.34   897.5 2022.21
     905 2024.08   912.5 2028.83   922.5 2039.87   926.6 2043.24   976.6  2065.2
#Mann= 9 ,-1 , 0
       0      .1       0   99.21      .1       0  111.25     .05       0
     275     .06       0  438.75      .1       0  469.09      .1       0
     748    .045       0   776.6      .1       0  929.99      .1       0
Bank Sta=748,776.6
XS Rating Curve= 0 ,0
Exp/Cntr(USF)=0,0
Exp/Cntr=0.3,0.1

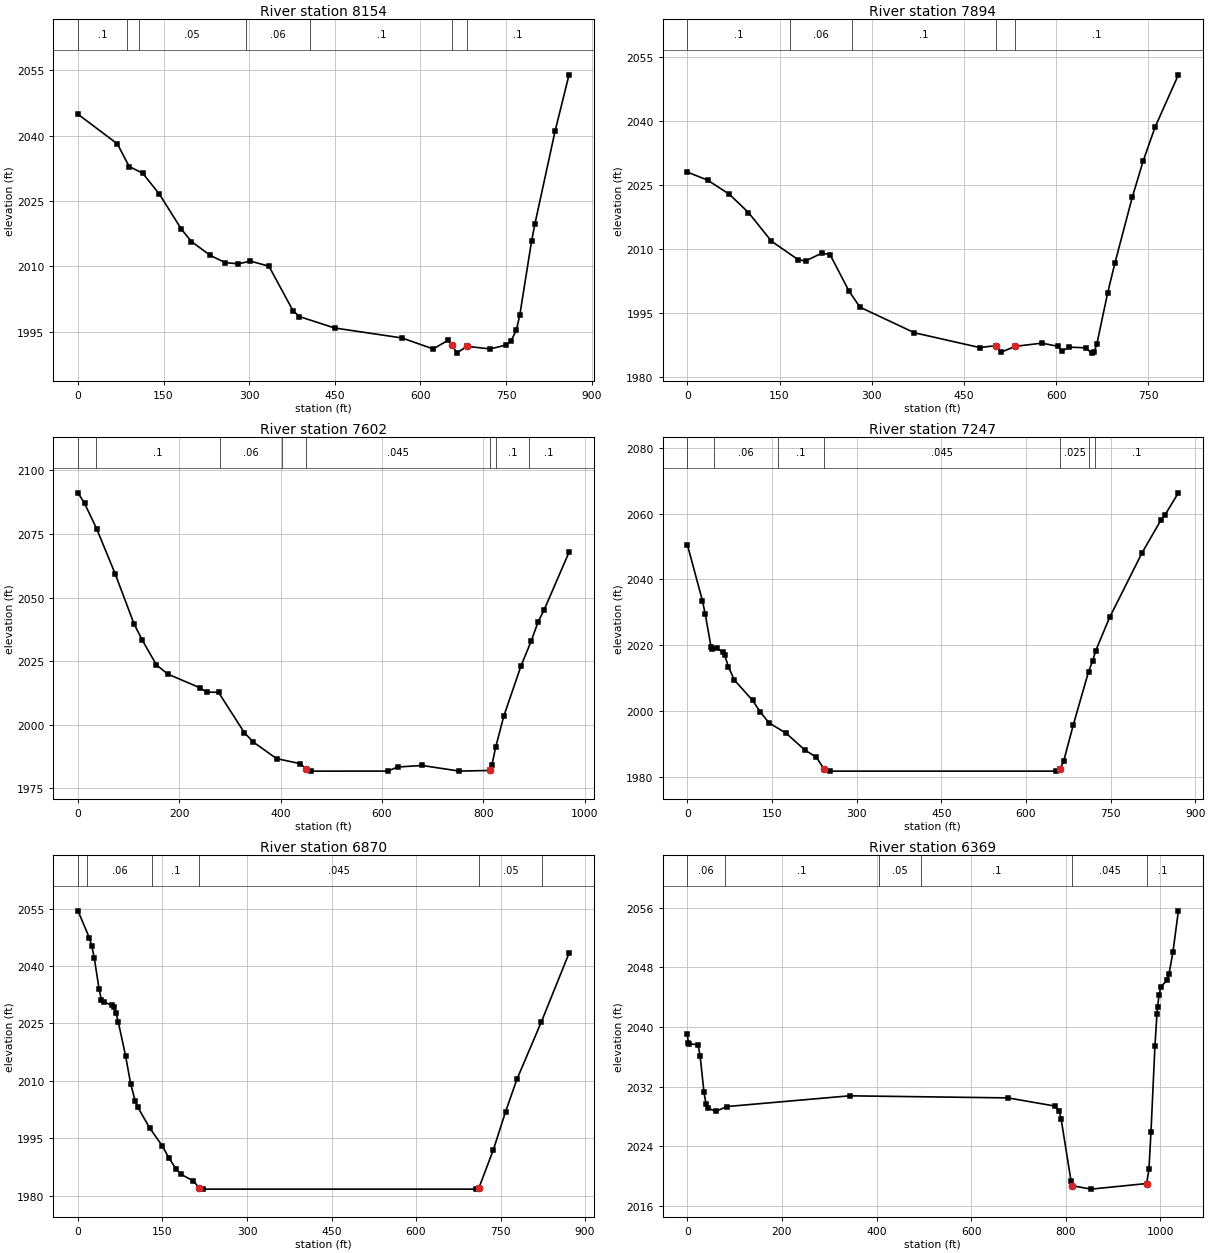
Type RM Length L Ch R = 1 ,8154    ,257.2,259.7,259.7
XS GIS Cut Line= 2
2450992.08708938546595.9159345322451402.58516764547352.099571623
#Sta/Elev= 30
       0 2044.87    69.1 2038.08    89.7 2032.89   113.3 2031.39   142.8 2026.54
   181.2 2018.55   198.9  2015.7   231.9 2012.53   257.9 2010.89     281  2010.6
   302.1 2011.23   334.6 2010.06   376.6 1999.91   387.7 1998.54   449.6 1995.91
   567.6 1993.63   622.4 1991.11   647.9 1993.05   656.1 1992.11   663.3 1990.15
   681.5 1991.71   722.5 1991.11   749.8 1992.01   758.9 1992.99     768 1995.35
   774.1 1998.81   794.7 2015.73   800.6 2019.72     836 2041.01   860.4  2053.9
#Mann= 7 ,-1 , 0
       0      .1       0    86.7     .06       0   106.5     .05       0
  293.84     .06       0  407.21      .1       0   656.1    .045       0
   681.5      .1       0
Bank Sta=656.1,681.5
XS Rating Curve= 0 ,0
Exp/Cntr=0.3,0.1

Type RM Length L Ch R = 1 ,7894    ,367.1,291.9,313.5
XS GIS Cut Line= 2
2450864.01065898546833.1663405832451207.11428581547554.777076262
#Sta/Elev= 30
       0 2028.05    32.9 2026.17    68.3 2022.85    99.4 2018.56   136.8 2011.83
   180.5 2007.46   192.5 2007.19   218.9 2009.02   232.2 2008.67   263.2 2000.06
   280.9 1996.33   369.5 1990.31   475.8 1986.84   502.4 1987.29   510.7 1985.76
   533.91987.132   576.7 1987.87   602.5 1987.15   609.7 1986.01   621.2 1986.94
   648.6 1986.77   657.7 1985.53   661.8 1985.73   666.3 1987.67     684 1999.74
   695.7 2006.68     724 2022.17   741.8  2030.7   760.9 2038.56     799  2050.9
#Mann= 5 ,-1 , 0
       0      .1       0  166.38     .06       0  268.14      .1       0
   502.4    .045       0   533.9      .1       0
Bank Sta=502.4,533.9
XS Rating Curve= 0 ,0
Exp/Cntr=0.3,0.1

Type RM Length L Ch R = 1 ,7602    ,330.5,355.3,375.8
XS GIS Cut Line= 2
2450399.63414006547037.8542771032451094.51058269547713.046004257
#Sta/Elev= 30
       0 2091.13      13 2086.99    36.9 2077.01    73.7 2059.16   110.5 2039.71
     127 2033.19   154.9 2023.51   177.2 2019.91   240.5 2014.54     254 2012.81
   277.3 2012.76   328.2  1996.9   345.9 1993.22   391.8 1986.71   438.6 1984.71
   450.3 1982.58   460.7 1981.78   611.1 1981.79   630.9  1983.4     679    1984
   752.5 1981.79   812.51982.043   816.6 1984.02   824.2  1991.2   840.2 2003.37
   874.2 2023.12     894 2032.76   908.1 2040.52   919.9 2045.18   968.9 2067.77
#Mann= 8 ,-1 , 0
       0     .12       0   35.62      .1       0  279.84     .06       0
  401.94    .025       0   450.3    .045       0   812.5    .025       0
   825.1      .1       0  890.38      .1       0
Bank Sta=450.3,812.5
XS Rating Curve= 0 ,0
Exp/Cntr(USF)=0,0
Exp/Cntr=0.3,0.1

Type RM Length L Ch R = 1 ,7247    ,495.3,376.4,251.5
XS GIS Cut Line= 2
2450290.36150796547338.039513264 2450834.2892931548017.395806366
#Sta/Elev= 30
       0 2050.53    26.7 2033.56    31.8 2029.37    42.1  2019.4    43.6    2019
    52.3 2019.04    63.5 2017.91    66.3 2016.91    72.8 2013.43    83.4 2009.42
   115.8 2003.23   128.9 1999.82   144.6 1996.47   175.3 1993.24   208.6 1988.15
   228.5 1986.02   241.9 1982.54   252.2 1981.78   653.4 1981.78   661.1 1982.54
   667.2 1984.97   683.8 1995.68     711 2011.94   718.5 2015.35   723.8 2018.36
   748.4 2028.45   806.2 2048.16     839  2057.9   846.6 2059.58   870.3 2066.28
#Mann= 7 ,-1 , 0
       0      .1       0   47.47     .06       0  159.92      .1       0
   241.9    .045       0   661.1    .025       0  711.48      .1       0
  722.16      .1       0
Bank Sta=241.9,661.1
XS Rating Curve= 0 ,0
Exp/Cntr=0.3,0.1

Type RM Length L Ch R = 1 ,6870    ,658.6,389.4,157.5
XS GIS Cut Line= 2
2449899.92227167547796.4225094152450711.67554089548113.659419223
#Sta/Elev= 30
       0  2054.4    20.2 2047.35    24.5 2045.27    28.8 2042.21    37.4 2034.05
    41.7 2031.13      46 2030.62    59.7 2029.79    63.2  2029.3    67.4 2027.85
    71.7 2025.28    84.4 2016.64    93.6  2009.2   101.8 2004.66   105.7 2003.27
   127.6 1997.66   149.6 1993.08   161.9 1989.79   174.8 1986.93   183.4 1985.61
   204.9  1983.9   215.6 1982.02   222.1 1981.78   707.3 1981.78   711.6  1982.1
   737.4 1992.11   758.9 2001.97   779.1 2010.47   822.4 2025.41   871.5 2043.32
#Mann= 6 ,-1 , 0
       0      .1       0   16.58     .06       0  131.92      .1       0
   215.6    .045       0   711.6     .05       0  823.92      .1       0
Bank Sta=215.6,711.6
XS Rating Curve= 0 ,0
Exp/Cntr(USF)=0,0
Exp/Cntr=0.3,0.1

Type RM Length L Ch R = 1 ,6369    ,148.3,151.4,158.4
XS GIS Cut Line= 3
2449796.82238883548140.8943236472450534.65410993548341.589630627
2450793.73049475548254.070195993
#Sta/Elev= 30
       0 2039.02       2 2037.85     3.2 2037.76    22.7  2037.6    26.9 2036.16
    35.2 2031.22    39.3  2029.7    43.4 2029.11      60 2028.66    83.8 2029.31
   342.9 2030.75   678.2 2030.47   776.3 2029.38   785.8 2028.77   790.1 2027.66
     811 2019.36   814.2 2018.66   853.4 2018.21   970.9 2018.96   975.8 2020.85
   980.1 2025.84   988.5  2037.4   992.7 2041.71   994.1 2042.67   997.2 2044.31
  1001.2 2045.39  1013.8 2046.28  1018.1 2047.09  1026.5 2050.04  1038.1 2055.61
#Mann= 6 ,-1 , 0
       0     .06       0   78.94      .1       0  406.18     .05       0
  494.08      .1       0   814.2    .045       0   970.9      .1       0
Bank Sta=814.2,970.9
XS Rating Curve= 0 ,0
Exp/Cntr=0.3,0.1

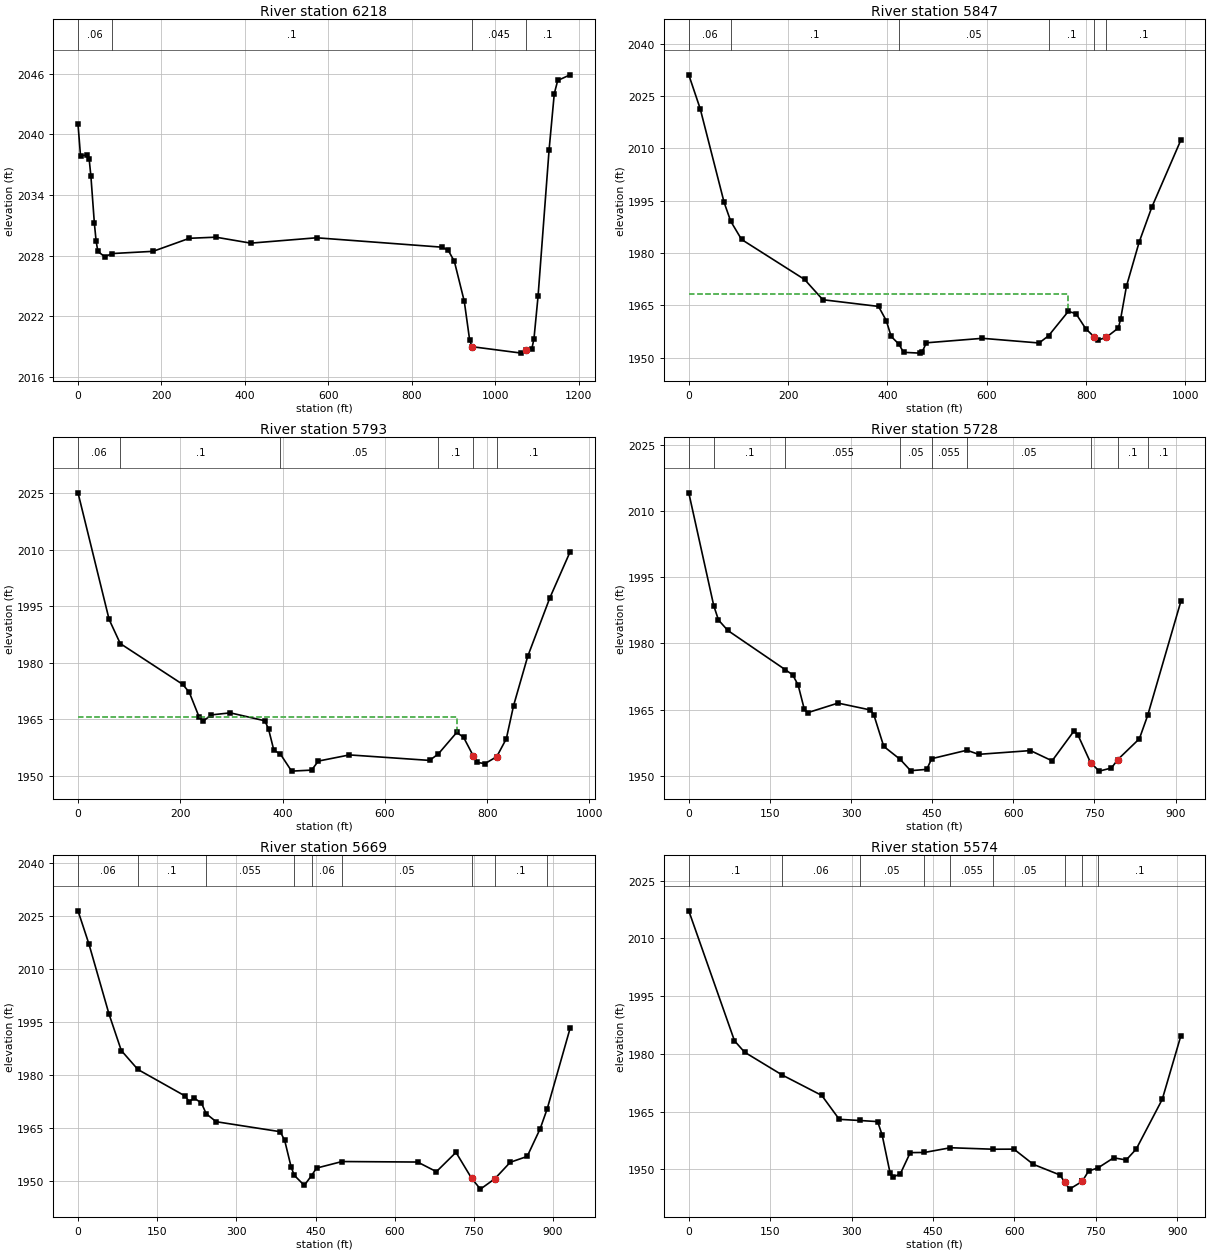
Type RM Length L Ch R = 1 ,6218    ,353.5,369.7,427
XS GIS Cut Line= 5
2449791.73268176  548145.68276592450033.49163433548210.411486943
2450550.58717179548352.5567970242450623.33870845548464.482238031
 2450874.0516963548398.446227837
#Sta/Elev= 30
       0 2040.99       6 2037.88    22.6 2037.97    26.8 2037.52    30.9 2035.85
    39.2  2031.2    43.3 2029.48    47.5 2028.43      64 2027.89    81.5 2028.21
   179.9 2028.43   266.9 2029.72   330.3 2029.83     414 2029.24   571.7 2029.77
   872.6 2028.84   887.3 2028.53     902 2027.44   925.8 2023.48   938.8 2019.61
   944.72018.995  1062.9 2018.36  1073.62018.637  1087.7 2018.79  1092.8 2019.78
  1102.6 2023.98  1129.1 2038.49  1141.5 2044.03  1149.7 2045.33  1179.3 2045.89
#Mann= 4 ,-1 , 0
       0     .06       0    81.5      .1       0   944.7    .045       0
  1073.6      .1       0
Bank Sta=944.7,1073.6
XS Rating Curve= 0 ,0
Exp/Cntr(USF)=0,0
Exp/Cntr=0.3,0.1

Type RM Length L Ch R = 1 ,5847    ,53.8,54.3,55.5
XS GIS Cut Line= 4
 2449752.4963141548297.7689374542450272.97264472548529.603527196
2450455.67672537548587.9460067342450612.28022308548755.296803303
#Sta/Elev= 30
       0 2031.13    23.1 2021.35    71.2 1994.51    84.4 1989.14   106.3  1983.9
   233.2 1972.42   269.9 1966.61   382.1 1964.69   397.7 1960.61   407.5  1956.1
   423.3 1953.83   432.4 1951.52   465.3 1951.29   469.7 1951.56   478.4 1954.25
   591.3 1955.54   705.4  1954.2   724.5 1956.27   764.2 1963.26   779.6 1962.63
   799.4 1958.28   816.9 1955.88   824.9 1955.08   840.3 1955.78   865.1 1958.51
   869.6 1961.09   881.4 1970.52   906.9 1983.13   932.4 1993.16   990.8 2012.39
#Mann= 6 ,-1 , 0
       0     .06       0    84.4      .1       0   423.3     .05       0
   724.5      .1       0   816.9    .045       0   840.3      .1       0
#XS Ineff= 2 , 0
          764.51 1968.34
Permanent Ineff=
       F       F
Bank Sta=816.9,840.3
XS Rating Curve= 0 ,0
Exp/Cntr(USF)=0,0
Exp/Cntr=0.3,0.1

Type RM Length L Ch R = 1 ,5793    ,66.2,65.3,64.7
XS GIS Cut Line= 3
2449753.67432091548326.4506793082450398.13315921548602.346456488
2450572.93735391548796.105322905
#Sta/Elev= 30
       0 2025.15    60.8 1991.49    82.6 1985.08   204.4 1974.26   217.4 1972.16
   236.7 1965.58   244.5 1964.45   260.9 1966.12   297.7 1966.66   365.4 1964.55
   372.5 1962.35   382.8 1956.77   395.8 1955.67   417.6 1951.17   456.7 1951.44
   469.8 1953.84   530.7 1955.48   687.3 1954.02   704.3 1955.72   740.4 1961.45
   753.8 1960.17   772.61955.272   780.8 1953.48   795.6 1953.16   818.71955.013
   837.4 1959.78   851.6  1968.6   879.2 1981.66   922.3 1997.17     962 2009.44
#Mann= 6 ,-1 , 0
       0     .06       0    82.6      .1       0   395.8     .05       0
   704.3      .1       0   772.6    .045       0   818.7      .1       0
#XS Ineff= 2 , 0
          741.51 1965.67
Permanent Ineff=
       F       F
Bank Sta=772.6,818.7
XS Rating Curve= 0 ,0
Exp/Cntr(USF)=0,0
Exp/Cntr=0.3,0.1

Type RM Length L Ch R = 1 ,5728    ,65.8,59.6,48.5
XS GIS Cut Line= 3
2449764.06253091548354.2285359782450265.46677682548563.039332365
2450519.92045608548827.062429801
#Sta/Elev= 30
       0 2014.06    46.2  1988.5    54.9 1985.27    72.2  1982.9   178.6 1974.01
   192.2 1972.85   202.2 1970.54   213.6 1965.08   219.6 1964.28   275.9 1966.46
     336  1964.9   342.1 1963.84   360.5 1956.66   391.1  1953.7   410.2 1951.16
     440 1951.46   449.2 1953.88   514.2 1955.79   535.9 1954.86   631.8 1955.71
   671.8 1953.39   712.2 1960.14   719.3 1959.32   742.9 1952.99   758.9 1951.06
   781.6 1951.77   792.8 1953.62   833.2 1958.39   848.5 1963.66   909.8 1989.46
#Mann= 9 ,-1 , 0
       0     .06       0    46.2      .1       0   178.6    .055       0
   391.1     .05       0   449.2    .055       0   514.2     .05       0
   742.9    .045       0   792.8      .1       0   848.5      .1       0
Bank Sta=742.9,792.8
XS Rating Curve= 0 ,0
Exp/Cntr=0.3,0.1

Type RM Length L Ch R = 1 ,5669    ,95,94.4,96.3
XS GIS Cut Line= 2
2449720.87329731 548380.537232662450525.26431431 548851.45882303
#Sta/Elev= 30
       0 2026.55    20.7 2017.13    58.6 1997.34      82 1986.94   113.4 1981.58
   202.6 1974.08   210.7 1972.48     220 1973.49   233.9 1972.04   242.8 1969.04
   261.7 1966.77   383.1 1963.94   391.5 1961.47   403.6    1954   409.5 1951.61
   428.6 1948.72   442.5 1951.52   451.8 1953.62   500.1 1955.48   643.3 1955.34
   678.9 1952.61     716 1958.08   745.7 1950.71   762.3 1947.66   789.5 1950.59
   818.8 1955.27   850.9 1956.93   875.6 1964.82   888.9 1970.46   932.1 1993.21
#Mann= 9 ,-1 , 0
       0     .06       0   113.4      .1       0   242.8    .055       0
   409.5     .05       0   442.5     .06       0   500.1     .05       0
   745.7    .045       0   789.5      .1       0   888.9      .1       0
Bank Sta=745.7,789.5
XS Rating Curve= 0 ,0
Exp/Cntr=0.3,0.1

Type RM Length L Ch R = 1 ,5574    ,90,97,104.3
XS GIS Cut Line= 2
2449709.95467298548484.8209012212450493.72266778548940.087875594
#Sta/Elev= 30
       0 2017.16    84.2 1983.38   102.7 1980.43   172.1 1974.49     245 1969.18
   277.2 1962.97   314.7 1962.67   347.9 1962.38   356.2 1958.91     371 1948.91
   375.6 1947.96   389.5 1948.75     408 1954.32   434.2 1954.36   482.1 1955.59
   560.6  1955.2     599 1955.22   634.7 1951.27   683.9  1948.5   692.7 1946.59
   701.4 1944.83   724.9 1946.85   724.9 1946.86   736.4 1949.52   754.1 1950.37
   782.7 1952.97   805.8 1952.41   824.3 1955.25   872.2 1968.16   906.4 1984.64
#Mann= 9 ,-1 , 0
       0      .1       0   172.1     .06       0   314.7     .05       0
   434.2    .035       0   482.1    .055       0   560.6     .05       0
   692.7    .045       0   724.9      .1       0   754.1      .1       0
Bank Sta=692.7,724.9
XS Rating Curve= 0 ,0
Exp/Cntr(USF)=0,0
Exp/Cntr=0.3,0.1

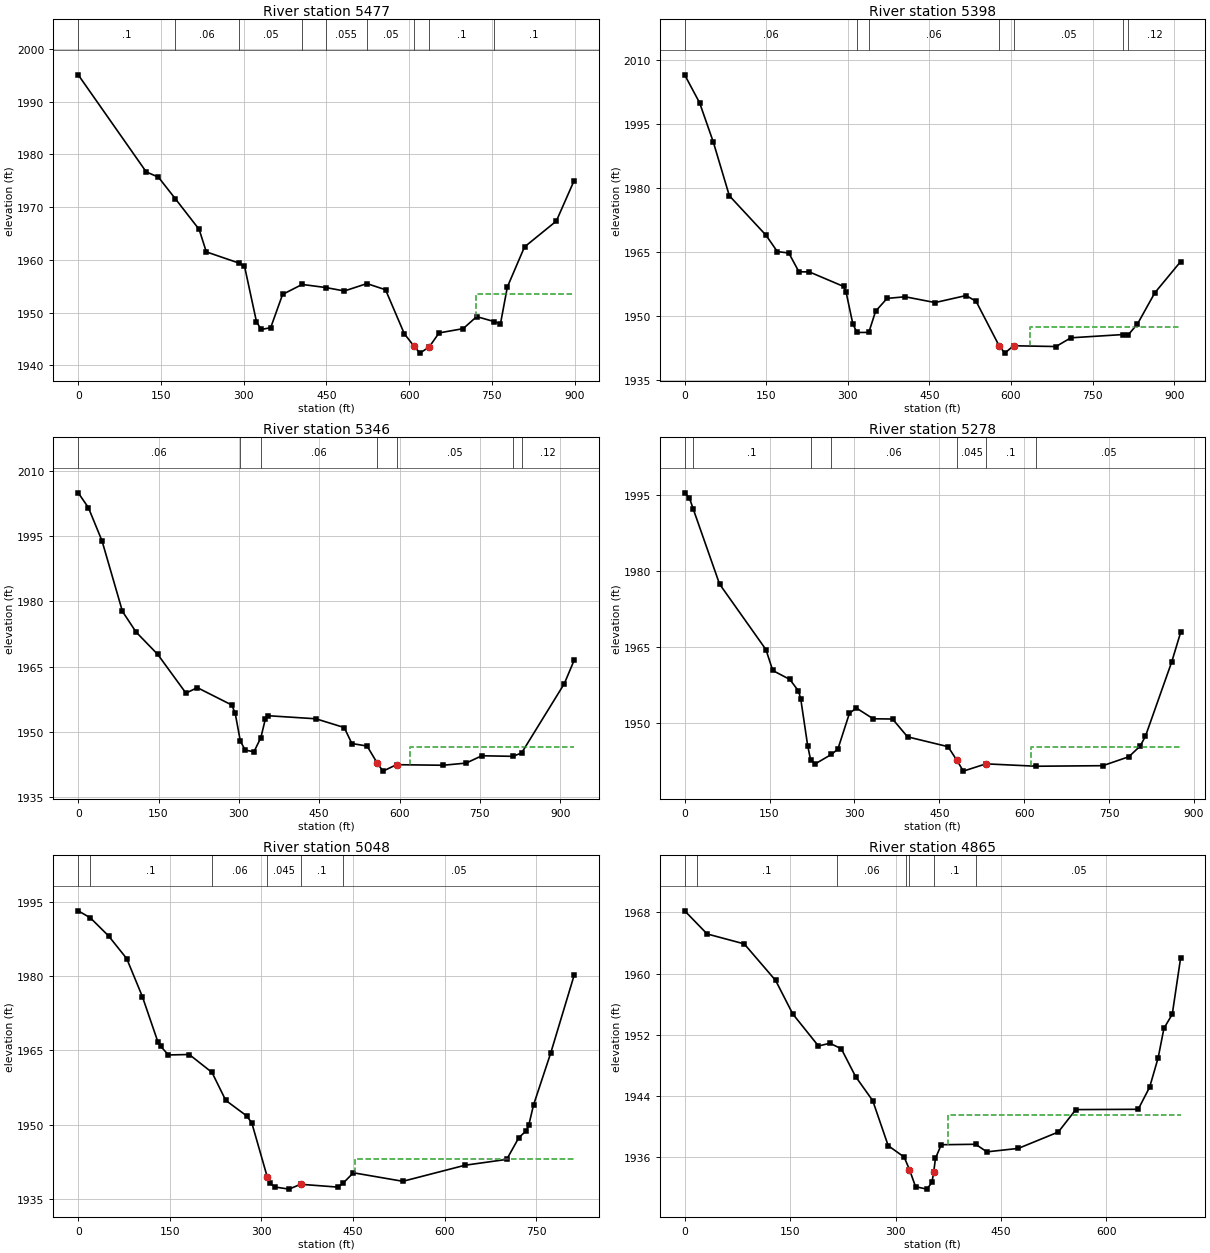
Type RM Length L Ch R = 1 ,5477    ,75.5,79.7,88.4
XS GIS Cut Line= 3
2449695.96425909548624.0513888182450157.04319871548813.321921652
2450441.67161193549095.209063919
#Sta/Elev= 30
       0 1995.07   123.3 1976.67   145.3 1975.68   175.9  1971.6   219.2 1965.77
   232.2 1961.51   291.9 1959.37   301.4 1958.83   323.1 1948.29   331.6  1946.8
   348.9 1947.14   370.5 1953.45   405.9 1955.34   448.8 1954.75   482.5  1954.1
   523.4  1955.5   557.1 1954.33   591.2 1945.98   608.6 1943.65   619.5 1942.32
   636.5 1943.52   654.1 1946.15   697.8 1946.96   722.3 1949.24   754.1  1948.3
   765.4 1947.86   777.9 1954.85     809 1962.45   866.7 1967.35     899 1975.03
#Mann= 9 ,-1 , 0
       0      .1       0   175.9     .06       0   291.9     .05       0
   405.9    .035       0   448.8    .055       0   523.4     .05       0
   608.6    .045       0   636.5      .1       0   754.1      .1       0
#XS Ineff= 2 , 0
                           721.3         1953.47
Permanent Ineff=
       F       F
Bank Sta=608.6,636.5
XS Rating Curve= 0 ,0
Exp/Cntr=0.5,0.3

Type RM Length L Ch R = 1 ,5398    ,53,51.8,53.8
XS GIS Cut Line= 4
2449668.58756481  548718.41909762450138.09109793548869.871850219
2450297.11648818549153.0884976172450389.50266728549168.233772879
#Sta/Elev= 30
       0 2006.59    27.5    2000    52.7 1990.77    82.1 1978.18   149.4 1968.92
   170.4 1965.05   191.4 1964.73     210 1960.31   229.2 1960.28   292.3 1956.86
   296.5 1955.68   309.1  1948.1   316.7 1946.05   338.5 1946.07   351.1 1951.06
   372.1 1954.06   405.4 1954.44   460.4 1953.08   517.4 1954.73   535.8 1953.37
     578 1942.95   588.6  1941.2   604.6 1942.93   682.6 1942.75   710.1  1944.8
   806.4 1945.57   815.6 1945.51   832.5 1948.05   864.4 1955.38   911.8  1962.7
#Mann= 7 ,-1 , 0
       0     .06       0   316.7     .05       0   338.5     .06       0
     578    .045       0   604.6     .05       0   806.4      .1       0
   815.6     .12       0
#XS Ineff= 2 , 0
                          635.27          1947.3
Permanent Ineff=
       F       F
Bank Sta=578,604.6
XS Rating Curve= 0 ,0
Exp/Cntr(USF)=0,0
Exp/Cntr=0.5,0.3

Type RM Length L Ch R = 1 ,5346    ,67.7,68.1,70.2
XS GIS Cut Line= 4
2449664.76464125548739.7118432512450082.84611133 548885.34848578
 2450269.6582352549178.4845312112450403.32723204549202.084525622
#Sta/Elev= 30
       0 2004.94      19 2001.54    44.5 1993.88    82.6 1977.69     108 1972.95
   148.6 1967.79   201.2  1958.9   222.4 1960.17   286.8 1956.17   293.1 1954.28
   302.8 1947.87   311.9 1945.81   328.2 1945.43     341 1948.66   349.4 1952.91
   353.7 1953.72   443.8 1953.01   496.7    1951     511 1947.32   539.4 1946.75
   558.4 1942.82   569.1 1940.98   594.4 1942.46   681.7 1942.33   724.4 1942.83
   753.7 1944.51   811.7 1944.38     828 1945.16   907.7 1961.08   926.1 1966.46
#Mann= 7 ,-1 , 0
       0     .06       0   302.8     .05       0     341     .06       0
   558.4    .045       0   594.4     .05       0   811.7      .1       0
     828     .12       0
#XS Ineff= 2 , 0
                          619.93         1946.51
Permanent Ineff=
       F       F
Bank Sta=558.4,594.4
XS Rating Curve= 0 ,0
Exp/Cntr=0.5,0.3

Type RM Length L Ch R = 1 ,5278    ,244.3,229.7,202.7
XS GIS Cut Line= 4
2449678.60395318548865.1187630482450037.09261863548945.540174689
 2450260.6368815549252.2319987432450390.12898499 549254.95814829
#Sta/Elev= 30
       0 1995.33     8.3 1994.34      15 1992.19    61.6  1977.4   143.6 1964.52
   155.6 1960.41   185.8 1958.65     201  1956.4   205.1 1954.83   217.4  1945.6
   222.6 1942.81   230.4 1942.04   259.4 1943.92   270.7 1944.95   291.2 1952.02
   303.5 1953.02   333.1 1950.92   367.4 1950.87   393.8 1947.37   465.3 1945.44
   481.2 1942.73   492.4 1940.63   532.4 1942.06   621.6 1941.59   738.9  1941.7
     785 1943.46     805 1945.57   814.3 1947.51   860.8 1962.14   876.4 1967.89
#Mann= 7 ,-1 , 0
       0     .12       0      15      .1       0   222.6     .05       0
   259.4     .06       0   481.2    .045       0   532.4      .1       0
   621.6     .05       0
#XS Ineff= 2 , 0
                          612.27         1945.44
Permanent Ineff=
       F       F
Bank Sta=481.2,532.4
XS Rating Curve= 0 ,0
Exp/Cntr(USF)=0,0
Exp/Cntr=0.3,0.1

Type RM Length L Ch R = 1 ,5048    ,198.2,182.7,157.4
XS GIS Cut Line= 3
2449632.25941088549085.9368763672450159.76934825549280.856568988
2450409.21203182549283.582718535
#Sta/Elev= 30
       0 1993.15    19.7 1991.75    49.6  1988.1    79.4  1983.5     105 1975.84
   130.6 1966.62   134.8 1965.83   147.6 1964.05   181.8 1964.14     219 1960.52
   241.5 1954.88   275.6 1951.76   284.1 1950.35   309.7 1939.31   313.9 1938.12
   322.5 1937.38   345.2 1936.96   363.9 1937.94   424.8 1937.37   433.3 1938.13
   450.4 1940.26   531.4 1938.54   633.4 1941.79   701.4 1942.96   721.4 1947.38
   733.4 1948.73   737.4 1949.81   745.3 1953.95   773.4 1964.42   811.8 1980.15
#Mann= 6 ,-1 , 0
       0     .12       0    19.7      .1       0     219     .06       0
   309.7    .045       0   363.9      .1       0   433.3     .05       0
#XS Ineff= 2 , 0
                          452.35         1943.02
Permanent Ineff=
       F       F
Bank Sta=309.7,363.9
XS Rating Curve= 0 ,0
Exp/Cntr(USF)=0,0
Exp/Cntr=0.3,0.1

Type RM Length L Ch R = 1 ,4865    ,105.9,108.1,110.2
XS GIS Cut Line= 2
 2449659.3198748549434.8340749482450354.10017502549312.452849668
#Sta/Elev= 30
       0 1968.21    31.9 1965.19    84.7 1963.89   129.4 1959.11   153.8 1954.73
   190.3 1950.55   206.6 1950.91   222.8 1950.19   243.1 1946.56   267.5 1943.41
   289.5 1937.53   312.2 1936.04   319.8  1934.4   328.4 1932.17   344.5 1931.85
   351.7 1932.72   354.3 1934.13   356.8 1935.89     365 1937.65   413.9 1937.71
   429.9 1936.72   474.6 1937.17   531.5 1939.31   556.4 1942.24   645.2 1942.28
   661.5 1945.19   673.6 1949.03   681.8 1952.87   693.6 1954.69   705.5 1962.05
#Mann= 7 ,-1 , 0
       0     .12       0   17.44      .1       0   216.1     .06       0
  315.42      .1       0   319.8    .045       0   354.3      .1       0
  414.75     .05       0
#XS Ineff= 2 , 0
                          374.41         1941.49
Permanent Ineff=
       F       F
Bank Sta=319.8,354.3
XS Rating Curve= 0 ,0
Exp/Cntr=0.5,0.3

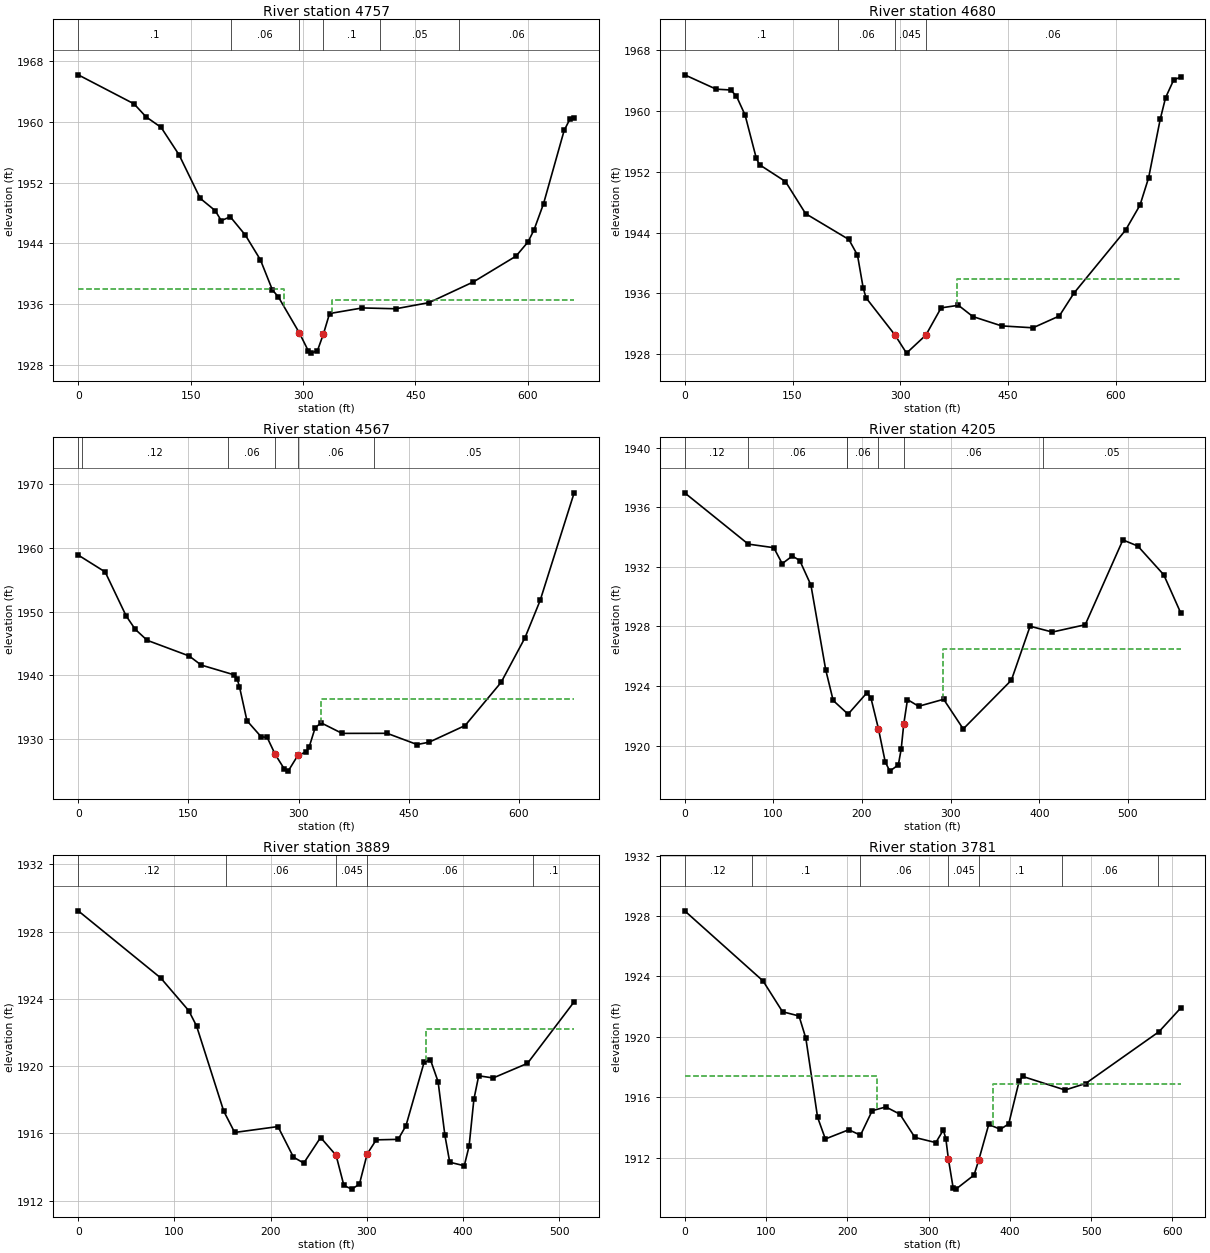
Type RM Length L Ch R = 1 ,4757    ,77,77.2,76.8
XS GIS Cut Line= 2
2449684.52670346549510.0440369092450344.02248164   549454.990074
#Sta/Elev= 30
       0 1966.23    74.5  1962.4    90.5 1960.69   110.6  1959.3   134.7 1955.66
   162.8 1949.94   182.8 1948.32   190.9    1947   202.9 1947.51     223  1945.1
   243.1 1941.84   259.1 1937.87   267.1 1936.94   295.2 1932.18   307.3 1929.78
   311.3 1929.53   319.3 1929.87   327.3 1932.08   335.4 1934.75   379.1 1935.49
   423.8 1935.38   468.1 1936.19   527.3 1938.92   584.2 1942.32   600.3  1944.2
   608.3  1945.8   620.9 1949.22   648.5 1958.91   655.9 1960.34   661.8 1960.57
#Mann= 6 ,-1 , 0
       0      .1       0  203.84     .06       0   295.2    .045       0
   327.3      .1       0  403.08     .05       0  508.05     .06       0
#XS Ineff= 2 , 0
          274.85    1938  339.26          1936.5
Permanent Ineff=
       F       F
Bank Sta=295.2,327.3
XS Rating Curve= 0 ,0
Exp/Cntr=0.5,0.3

Type RM Length L Ch R = 1 ,4680    ,114.7,112.8,110.8
XS GIS Cut Line= 2
2449686.92523912549581.4504891152450375.09450009549532.953296363
#Sta/Elev= 30
       0 1964.75    43.9 1962.86      64 1962.76      72 1961.95      84 1959.47
    99.6 1953.79   104.1 1952.93   140.2 1950.72   168.2  1946.5   228.4  1943.1
   240.4 1941.04   248.4 1936.69   252.4 1935.42   292.5 1930.55   308.6 1928.16
   335.6 1930.54   356.7 1934.11   380.8 1934.45   400.8 1932.97   440.9 1931.74
   484.5 1931.49   521.1 1933.04   541.6 1936.06   613.3 1944.33   633.4 1947.62
   645.4 1951.22   661.5  1958.9     669 1961.75   680.2 1964.07   689.9 1964.45
#Mann= 4 ,-1 , 0
       0      .1       0  213.17     .06       0   292.5    .045       0
   335.6     .06       0
#XS Ineff= 2 , 0
                          379.14         1937.95
Permanent Ineff=
       F       F
Bank Sta=292.5,335.6
XS Rating Curve= 0 ,0
Exp/Cntr=0.5,0.3

Type RM Length L Ch R = 1 ,4567    ,349.8,362.3,369.5
XS GIS Cut Line= 2
2449718.79109975549726.512050256 2450380.1172751549589.537475035
#Sta/Elev= 30
       0 1958.86    36.7 1956.21    65.3 1949.31    77.6 1947.22    93.9 1945.49
   151.1 1943.03   167.4 1941.61   212.4 1940.07   216.5  1939.4   219.6 1938.22
   229.8 1932.88   249.1 1930.36   257.3 1930.26   268.3 1927.59   280.5 1925.34
   285.9 1924.97   299.2 1927.45   310.4 1927.98   314.5 1928.74   322.7 1931.78
   330.8 1932.54   359.4 1930.89   420.7  1930.9   461.5 1929.14   477.9 1929.51
   526.9 1932.12   575.9 1938.89   608.4 1945.88   629.1 1951.74   675.4 1968.62
#Mann= 6 ,-1 , 0
       0      .1       0    5.43     .12       0  204.25     .06       0
   268.3    .045       0   299.2     .06       0  403.08     .05       0
#XS Ineff= 2 , 0
                          330.06         1936.29
Permanent Ineff=
       F       F
Bank Sta=268.3,299.2
XS Rating Curve= 0 ,0
Exp/Cntr=0.3,0.1

Type RM Length L Ch R = 1 ,4205    ,319.3,315.9,312.7
XS GIS Cut Line= 2
2449794.82349705549941.0397099312450328.82710521550107.570347591
#Sta/Elev= 30
       0 1936.96    71.7 1933.52   100.5 1933.28     110 1932.21   121.4 1932.72
   129.8 1932.42   142.4 1930.77   159.1 1925.08   167.5 1923.03   184.3 1922.11
   205.8 1923.56   210.2 1923.17   218.6 1921.12   226.2 1918.91   231.4 1918.29
     241 1918.71   244.2 1919.76   247.1 1921.44   251.3 1923.09   263.9 1922.64
   292.1 1923.11   314.2 1921.12   368.5 1924.39   389.6 1928.01   414.7 1927.62
   451.8 1928.11   494.3  1933.8   511.1 1933.39   540.4 1931.46   559.4 1928.92
#Mann= 7 ,-1 , 0
       0     .12       0   71.56     .06       0  182.57      .1       0
  183.25     .06       0   218.6    .045       0   247.1     .06       0
  404.59     .05       0
#XS Ineff= 2 , 0
                          291.85         1926.51
Permanent Ineff=
       F       F
Bank Sta=218.6,247.1
XS Rating Curve= 0 ,0
Exp/Cntr=0.3,0.1

Type RM Length L Ch R = 1 ,3889    ,117.2,107.5,95.4
XS GIS Cut Line= 4
2449674.97925221550246.9744198632449758.99550049550291.325115044
2450021.55781043550323.6163944432450145.84102556550229.642567846
#Sta/Elev= 30
       0 1929.24    85.7 1925.25   114.9  1923.3     123 1922.39   151.2 1917.33
   162.6 1916.06   207.6 1916.41   223.7 1914.59   234.4 1914.24   251.9 1915.76
     268  1914.7   276.1 1912.91   284.2 1912.69   292.2 1912.98   300.3 1914.78
   309.7 1915.62   332.5 1915.65   340.6 1916.46   359.5 1920.24     366 1920.39
     374 1919.08   381.1 1915.88   386.1 1914.29   401.2 1914.08   406.2 1915.24
   411.2 1918.03   416.2 1919.43   431.2  1919.3   466.9 1920.17   515.4 1923.83
#Mann= 5 ,-1 , 0
       0     .12       0  153.47     .06       0     268    .045       0
   300.3     .06       0  472.78      .1       0
#XS Ineff= 2 , 0
                          361.26         1922.23
Permanent Ineff=
       F       F
Bank Sta=268,300.3
XS Rating Curve= 0 ,0
Exp/Cntr=0.5,0.3

Type RM Length L Ch R = 1 ,3781    ,39.2,38.8,38.1
XS GIS Cut Line= 4
2449654.35715811550284.3521265512449889.87200624550440.161851006
2450075.67640929550370.3872017582450125.85143796 550251.22150866
#Sta/Elev= 30
       0 1928.34    96.4  1923.7   120.4 1921.66   140.7 1921.38   149.1  1919.9
   163.5 1914.68   173.1 1913.24   201.9 1913.85   216.3 1913.49   230.7 1915.11
   247.5 1915.36   264.8 1914.88   283.3 1913.34     309    1913   318.2 1913.83
   321.3 1913.27   324.4 1911.94   330.3 1910.01   333.8 1909.92     356 1910.85
   361.7 1911.82   374.1  1914.2   388.4 1913.88   398.7 1914.24   411.5 1917.06
   415.8 1917.38   468.1 1916.48   493.3 1916.91   583.6 1920.34   610.2  1921.9
#Mann= 7 ,-1 , 0
       0     .12       0   82.66      .1       0  215.41     .06       0
   324.4    .045       0   361.7      .1       0  463.69     .06       0
  582.93      .1       0
#XS Ineff= 2 , 0
          236.81  1917.4  379.75         1916.86
Permanent Ineff=
       F       F
Bank Sta=324.4,361.7
XS Rating Curve= 0 ,0
Exp/Cntr(USF)=0,0
Exp/Cntr=0.5,0.3