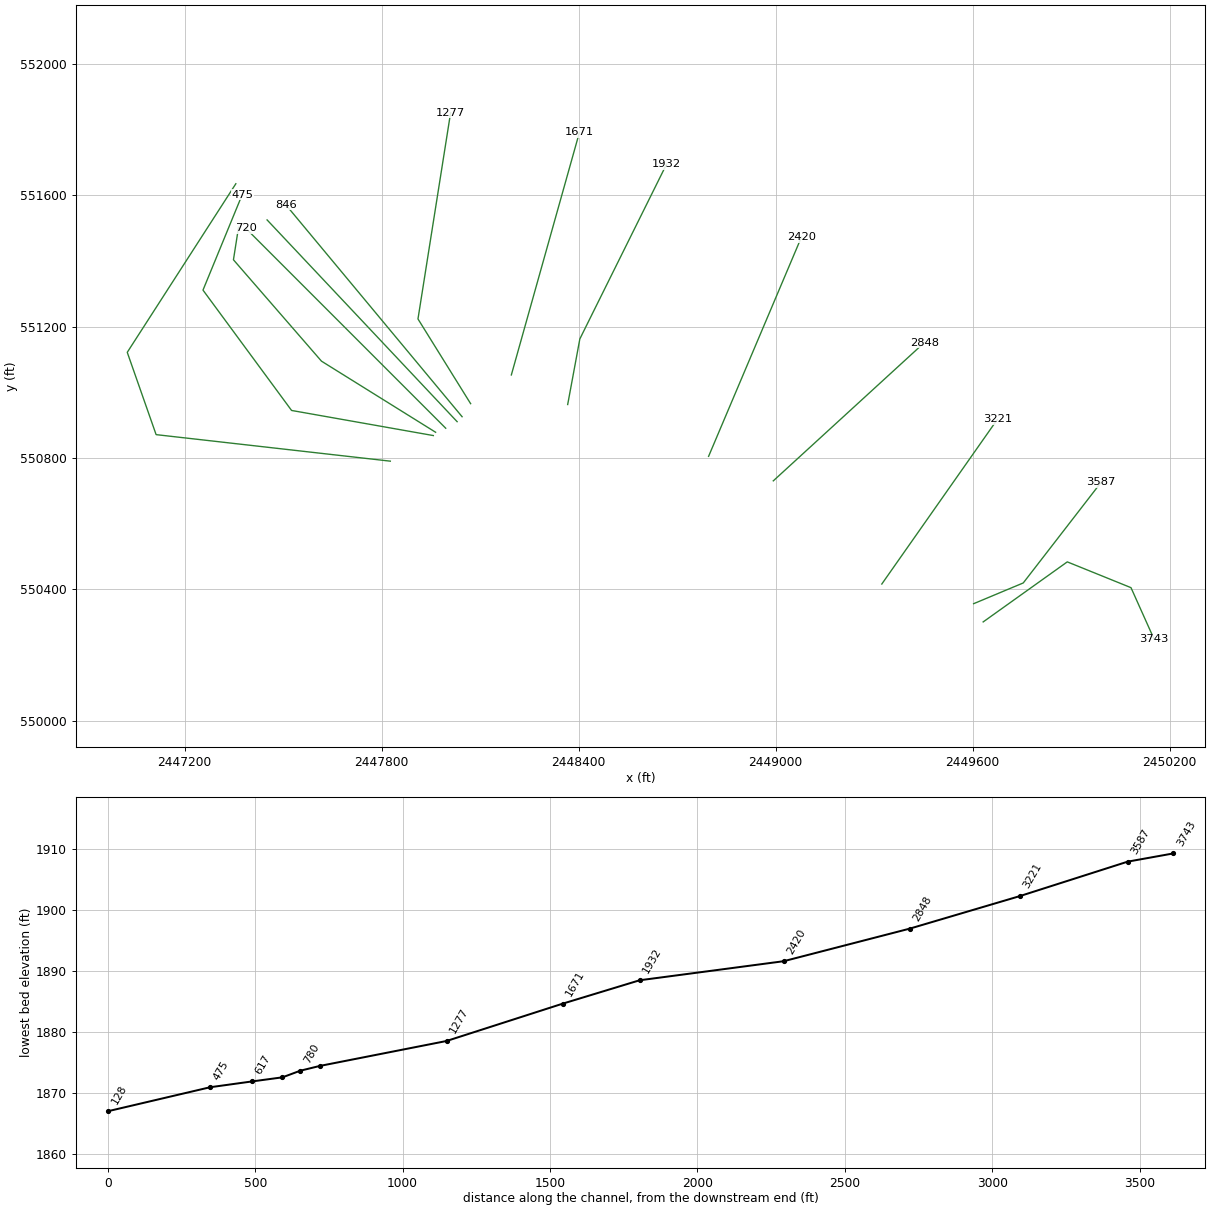
HEC-RAS study STONYRN.prj: STONYRN

--- STONYRN.g01 (geometry) --- (continued)

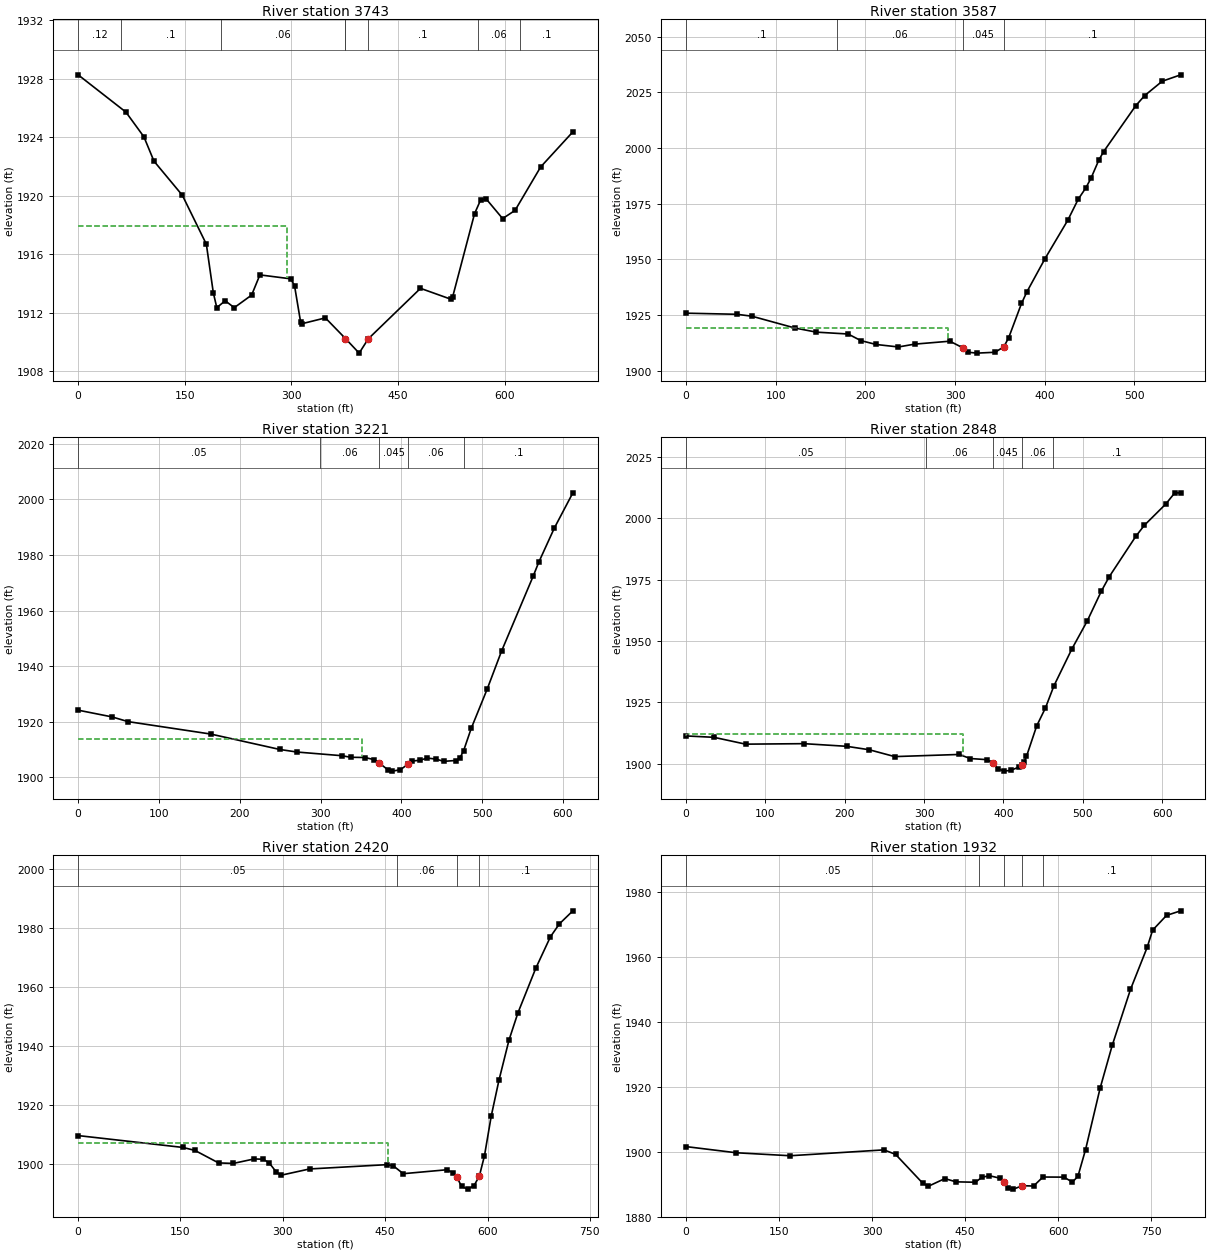
Type RM Length L Ch R = 1 ,3743    ,127.3,155.3,181.4
XS GIS Cut Line= 4
2449632.01312979550301.124184858 2449888.1547915550483.981237437
2450082.20024968550405.4233334542450152.47450053550248.697250409
#Sta/Elev= 30
       0 1928.27    67.2 1925.72    92.5 1924.03   106.6 1922.37   146.6 1920.03
   180.3 1916.69   190.1 1913.37     195 1912.35   206.8 1912.82   219.6 1912.35
     244 1913.21   255.6 1914.59   299.1 1914.32   304.3 1913.86   312.8 1911.39
   314.7 1911.25   347.7 1911.65   375.9 1910.24   395.2 1909.24   408.1 1910.22
   481.5 1913.67   524.1 1912.93   526.8  1913.1   557.5 1918.77   566.3 1919.74
   574.3 1919.76     597 1918.44   614.5    1919   650.5 1921.97   695.8 1924.37
#Mann= 8 ,-1 , 0
       0     .12       0   60.81      .1       0  200.32     .06       0
  375.02      .1       0   375.9    .045       0   408.1      .1       0
  562.35     .06       0  621.02      .1       0
#XS Ineff= 2 , 0
          293.87 1917.93
Permanent Ineff=
       F       F
Bank Sta=375.9,408.1
XS Rating Curve= 0 ,0
Exp/Cntr=0.5,0.3

Type RM Length L Ch R = 1 ,3587    ,363.7,365.9,366.7
XS GIS Cut Line= 3
2449602.91589795550356.5904812732449754.07964842550419.832824391
2449991.36246325550726.528880009
#Sta/Elev= 30
       0 1925.84    56.7 1925.34    73.5 1924.48   121.2  1919.2   145.3 1917.32
   180.8 1916.48     195 1913.51   212.1 1911.77   236.9 1910.66   254.9 1911.93
   294.2 1913.25   308.8 1910.26   314.8 1908.28   324.5 1907.89   344.7 1908.28
   354.5 1910.76   359.9 1914.89   374.1 1930.19   380.1  1935.4   400.3 1950.31
   425.7 1967.58   437.4 1977.07   445.9 1982.16   451.7 1986.55   460.2  1994.5
   465.6 1998.38   501.5 2019.05   511.5 2023.61     531 2030.04   551.6 2032.92
#Mann= 4 ,-1 , 0
       0      .1       0  168.43     .06       0   308.8    .045       0
   354.5      .1       0
#XS Ineff= 2 , 0
             292 1919.33
Permanent Ineff=
       F       F
Bank Sta=308.8,354.5
XS Rating Curve= 0 ,0
Exp/Cntr=0.3,0.1

Type RM Length L Ch R = 1 ,3221    ,377.3,373,367.4
XS GIS Cut Line= 2
 2449323.2971061550416.5708152582449675.05615728550917.654498827
#Sta/Elev= 30
       0 1924.17    41.9 1921.75    61.6 1920.06   164.1 1915.58   249.7 1910.03
   270.6 1909.12   326.2  1907.8   337.2 1907.23   354.7 1907.15   365.9 1906.41
   372.6 1905.16     384 1902.58   388.9 1902.25   398.7 1902.75   408.5 1904.81
   413.4 1905.88   423.1 1906.17     432 1906.96   442.7 1906.57   452.5 1905.77
   467.1 1906.07   472.2 1906.86   476.9 1909.52   486.4  1917.6   506.2 1931.77
   523.9 1945.37     563 1972.29   569.9  1977.3   589.3 1989.67   612.2 2002.32
#Mann= 5 ,-1 , 0
       0     .05       0  299.23     .06       0   372.6    .045       0
   408.5     .06       0  477.63      .1       0
#XS Ineff= 2 , 0
          351.43  1913.9
Permanent Ineff=
       F       F
Bank Sta=372.6,408.5
XS Rating Curve= 0 ,0
Exp/Cntr=0.3,0.1

Type RM Length L Ch R = 1 ,2848    ,420.2,428.2,438.6
XS GIS Cut Line= 2
     2448992.778      550730.7012449452.53576221551151.574235916
#Sta/Elev= 30
       0 1911.27    35.2 1910.71    75.1 1907.92   148.7 1908.12   202.5 1907.04
   230.9 1905.64     263 1902.85   344.1 1903.72   358.3 1902.06   379.4  1901.6
   386.6 1900.27   393.1 1897.87   400.7 1896.93   409.2 1897.25   420.2 1898.67
   423.4 1899.59   426.2 1900.82     429 1902.91   441.9 1915.37   452.8 1922.59
   463.6 1931.68     486 1946.57   505.5 1958.06   523.3 1970.24   533.4  1976.2
   566.7 1992.56   577.5 1997.08   604.6 2005.78   615.9 2010.32   623.3 2010.27
#Mann= 5 ,-1 , 0
       0     .05       0  302.55     .06       0   386.6    .045       0
   423.4     .06       0  462.73      .1       0
#XS Ineff= 2 , 0
          349.48 1912.07
Permanent Ineff=
       F       F
Bank Sta=386.6,423.4
XS Rating Curve= 0 ,0
Exp/Cntr=0.3,0.1

Type RM Length L Ch R = 1 ,2420    ,490.8,488.6,489.2
XS GIS Cut Line= 2
2448795.73118286550805.3668384982449078.50236854551473.109656104
#Sta/Elev= 30
       0 1909.73   153.7 1905.71   171.1 1904.71   205.8 1900.47   227.5  1900.3
   257.9 1901.82     271 1901.72   279.7 1900.57   290.3 1897.42     297 1896.28
   339.1 1898.42   453.4 1899.89   462.1 1899.44   476.5 1896.82   540.3 1898.15
     549 1897.22   554.8 1895.77     562 1892.51   570.7 1891.59   580.2 1892.74
   588.1 1896.07   595.5 1902.85   605.5 1916.39   616.8 1928.51   631.5  1942.1
   644.5 1951.26   670.6 1966.35   692.3 1977.12   705.4 1981.47   725.1 1985.88
#Mann= 4 ,-1 , 0
       0     .05       0  466.92     .06       0   554.8    .045       0
   588.1      .1       0
#XS Ineff= 2 , 0
          454.04 1907.23
Permanent Ineff=
       F       F
Bank Sta=554.8,588.1
XS Rating Curve= 0 ,0
Exp/Cntr=0.3,0.1

Type RM Length L Ch R = 1 ,1932    ,257.9,261.1,268.6
XS GIS Cut Line= 3
2448366.58705258550963.2049464792448403.61924088551163.012194569
2448667.80473615551695.349657043
#Sta/Elev= 30
       0 1901.58      81 1899.68     168 1898.76   319.2 1900.57   337.9 1899.18
   381.5 1890.33   390.6 1889.34   417.3 1891.72   435.2 1890.72   466.5 1890.59
     477 1892.09   488.9 1892.62   506.9  1891.8   512.8 1890.67   518.8 1888.76
   527.8 1888.47   542.5 1889.53   560.3 1889.42   575.5  1892.2   609.4 1892.17
   622.8 1890.63   631.8 1892.38   644.2 1900.68   667.5  1919.5   687.1 1932.76
   716.6 1950.03   743.4 1962.95   752.3  1968.3   774.7 1972.84   797.5 1974.25
#Mann= 5 ,-1 , 0
       0     .05       0  472.89     .06       0   512.8    .045       0
   542.5     .06       0  575.19      .1       0
Bank Sta=512.8,542.5
XS Rating Curve= 0 ,0
Exp/Cntr=0.3,0.1

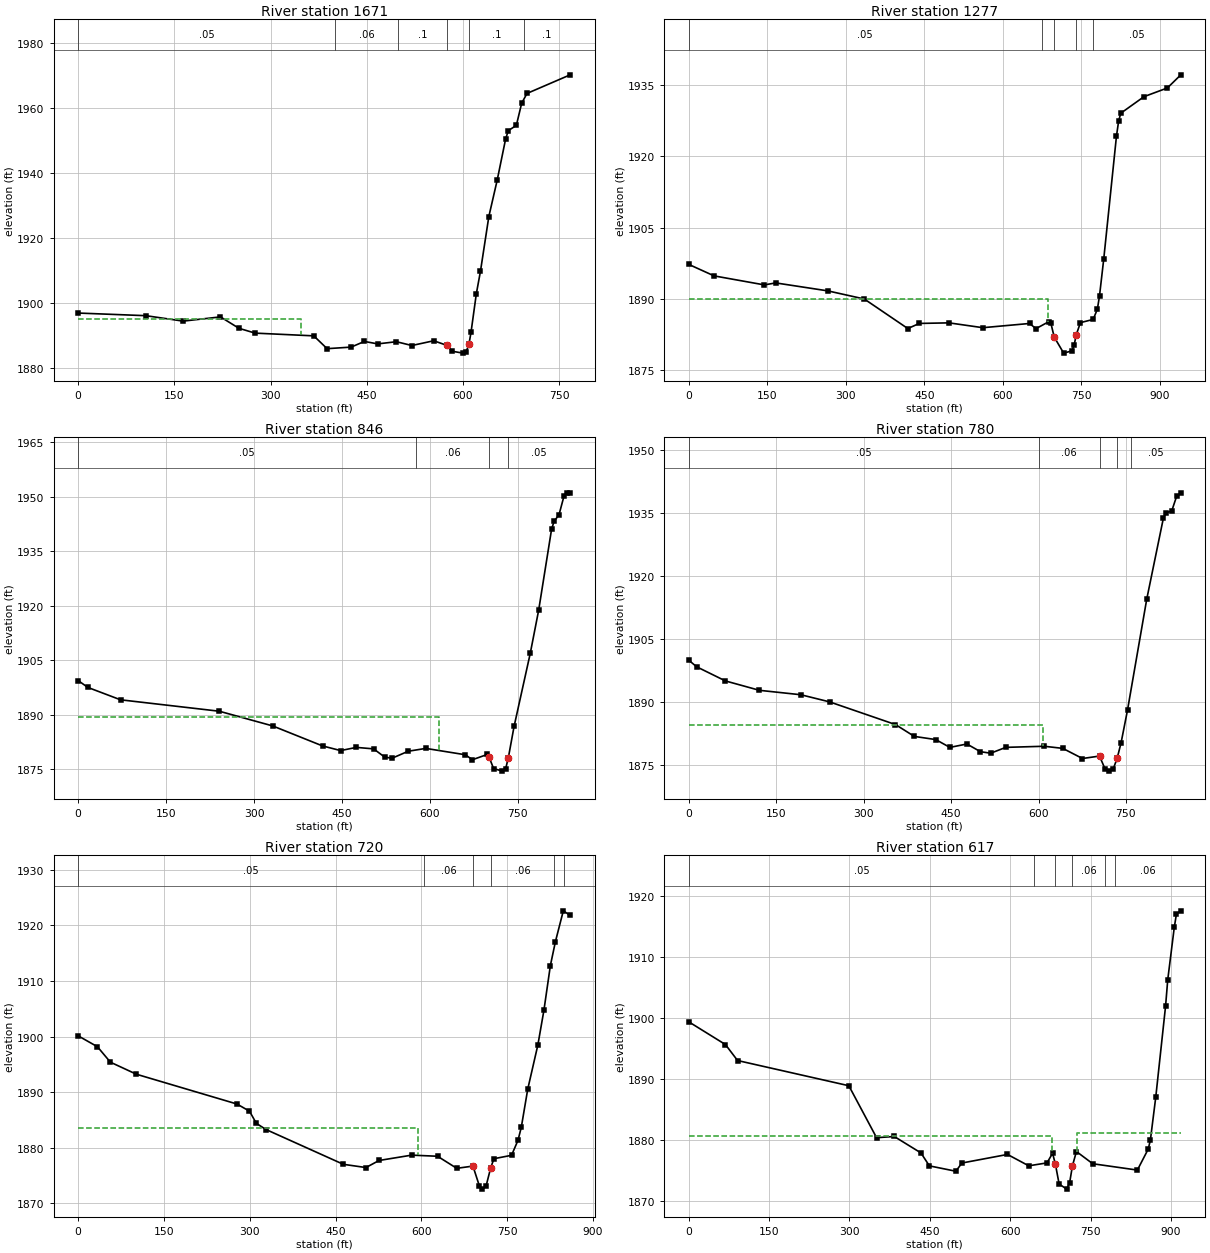
Type RM Length L Ch R = 1 ,1671    ,389.8,393.8,392.8
XS GIS Cut Line= 2
2448194.98123171551053.2551114852448402.27191495 551791.72817055
#Sta/Elev= 30
       0 1896.96   105.6 1896.15   163.7 1894.48   221.9 1895.78   250.7 1892.27
   275.9 1890.79   367.3 1889.95   388.1 1886.01   425.5 1886.49   446.2 1888.23
     467 1887.48   496.1 1888.15   520.2 1886.98   554.3 1888.44   574.5 1887.05
   583.3 1885.21     600 1884.64   604.5 1884.87   609.2 1887.37   612.4 1890.99
   620.7 1902.87   627.2 1909.86   640.2 1926.62   653.2 1937.78   666.4 1950.49
   670.6 1953.04   683.1 1954.65   691.4 1961.46   699.7 1964.47     767 1970.19
#Mann= 6 ,-1 , 0
       0     .05       0  400.44     .06       0  498.67      .1       0
   574.5    .045       0   609.2      .1       0  695.13      .1       0
#XS Ineff= 2 , 0
          347.67 1894.99
Permanent Ineff=
       F       F
Bank Sta=574.5,609.2
XS Rating Curve= 0 ,0
Exp/Cntr(USF)=0,0
Exp/Cntr=0.3,0.1

Type RM Length L Ch R = 1 ,1277    ,410.5,430.5,452.2
XS GIS Cut Line= 3
2448070.96707958550965.7844457752447910.62818333551223.807786855
2448010.10099953551852.329498827
#Sta/Elev= 30
       0 1897.23    48.4 1894.81   144.4 1892.91   166.1 1893.33   265.7 1891.65
   335.3 1889.94   418.5 1883.71   440.5 1884.79   497.2 1884.91   561.8 1883.89
   651.1 1884.78   663.4 1883.69   687.7 1885.15   691.6 1884.94   698.2 1881.92
   716.3 1878.53   732.1 1879.01   736.2 1880.19   740.4 1882.43   748.3 1884.96
   772.6 1885.63   780.7  1887.8   784.8 1890.65   792.9 1898.43   817.2 1924.32
   821.2 1927.37   825.3 1929.09   869.8 1932.59   914.4 1934.42   940.1 1937.19
#Mann= 5 ,-1 , 0
       0     .05       0  674.01     .06       0   698.2    .045       0
   740.4     .06       0  771.54     .05       0
#XS Ineff= 2 , 0
          686.99 1890.04
Permanent Ineff=
       F       F
Bank Sta=698.2,740.4
XS Rating Curve= 0 ,0
Exp/Cntr=0.3,0.1

Type RM Length L Ch R = 1 ,846     ,64.4,65.9,67
XS GIS Cut Line= 2
2448044.99612912550926.0487869842447508.35905548551571.303785348
#Sta/Elev= 30
       0  1899.4    16.4 1897.51    72.3 1894.09   240.8 1890.94   331.7  1886.9
   416.9 1881.38   447.7  1880.1   474.5 1880.98     504 1880.57   522.7 1878.32
   535.2 1877.98     563 1879.92     593  1880.7   660.4 1878.95   672.5 1877.58
   698.1 1879.05   700.9 1878.29   708.6 1875.15   723.6 1874.44   729.2 1875.12
   733.81878.172   743.5 1886.74   771.1 1906.87   785.5 1918.81   807.5 1941.09
   811.7 1943.22   820.2 1945.09   828.7 1950.24   833.5 1951.11   839.2 1950.97
#Mann= 4 ,-1 , 0
       0     .05       0  576.29     .06       0   700.9    .045       0
   733.8     .05       0
#XS Ineff= 2 , 0
          616.13 1889.33
Permanent Ineff=
       F       F
Bank Sta=700.9,733.8
XS Rating Curve= 0 ,0
Exp/Cntr(USF)=0,0
Exp/Cntr=0.3,0.1

Type RM Length L Ch R = 1 ,780     ,59.7,60.4,60.9
XS GIS Cut Line= 2
2448029.83840004550910.9844969012447451.13477808 551525.41568991
#Sta/Elev= 30
       0 1900.03    13.4 1898.47    62.9  1895.1   121.2 1892.87   192.2 1891.82
   241.6 1890.12   354.6 1884.73     387 1881.91   423.7 1881.16   447.9  1879.3
   477.1 1880.11   500.4 1878.28   517.9 1877.92   543.9 1879.31   609.8 1879.57
   641.6 1879.07   675.4 1876.66   704.6 1877.24   714.2 1874.16   720.9 1873.66
   727.9 1874.09     735 1876.76   741.7 1880.45   752.7 1888.21   785.6 1914.51
   814.2 1933.81   818.6 1935.09   828.4 1935.47   836.9 1938.98   844.1 1939.82
#Mann= 5 ,-1 , 0
       0     .05       0  600.01     .06       0   704.6    .045       0
     735     .06       0  758.82     .05       0
#XS Ineff= 2 , 0
          608.24 1884.54
Permanent Ineff=
       F       F
Bank Sta=704.6,735
XS Rating Curve= 0 ,0
Exp/Cntr(USF)=0,0
Exp/Cntr=0.3,0.1

Type RM Length L Ch R = 1 ,720     ,104.2,102.8,101.3
XS GIS Cut Line= 2
2447995.08565663550891.0395499812447386.79093684551499.334269772
#Sta/Elev= 30
       0 1900.14    33.7 1898.18    56.4  1895.4     102 1893.23   277.7 1887.88
   299.6 1886.59   311.6  1884.4   328.6 1883.29   463.7 1877.04   503.2 1876.46
   526.2 1877.73   583.1 1878.69   628.4 1878.49     662 1876.32   690.3 1876.72
   701.6 1873.14   706.9 1872.58   713.2 1873.11   721.4 1876.43     727 1878.05
   757.8 1878.66   769.1 1881.37   774.8 1883.67   786.1 1890.55   803.8 1898.49
   814.4 1904.73   825.7 1912.78   834.5 1917.07   848.3 1922.61   860.3 1921.79
#Mann= 6 ,-1 , 0
       0     .05       0  604.46     .06       0   690.3    .045       0
   721.4     .06       0  831.98     .05       0  849.34     .06       0
#XS Ineff= 2 , 0
          594.22 1883.56
Permanent Ineff=
       F       F
Bank Sta=690.3,721.4
XS Rating Curve= 0 ,0
Exp/Cntr(USF)=0,0
Exp/Cntr=0.3,0.1

Type RM Length L Ch R = 1 ,617     ,145.6,142.3,140.7
XS GIS Cut Line= 4
2447964.33925432550878.7300871042447616.74938874551095.258477045
2447348.64593692551404.0129937632447364.14456334551503.014298021
#Sta/Elev= 30
       0  1899.4    68.4 1895.67    91.1 1893.04   298.8  1888.9   350.6 1880.36
   383.6 1880.56   433.4 1877.86   449.2 1875.73   498.6 1874.85   509.9  1876.2
     595 1877.61   634.7 1875.74   668.7 1876.22   679.2  1877.8   684.5 1875.98
   691.4 1872.76   705.4 1871.91     711 1872.95   716.3 1875.75   723.7 1878.09
   754.2 1876.08   837.5 1875.04   857.8  1878.5   861.8 1879.98   871.8 1887.01
   890.2 1902.03   894.2 1906.33   906.4 1914.92   910.4 1917.12   918.6 1917.64
#Mann= 6 ,-1 , 0
       0     .05       0  645.38     .06       0   684.5    .045       0
   716.3     .06       0  777.73      .1       0  796.47     .06       0
#XS Ineff= 2 , 0
          678.35 1880.59   724.8          1881.2
Permanent Ineff=
       F       F
Bank Sta=684.5,716.3
XS Rating Curve= 0 ,0
Exp/Cntr(USF)=0,0
Exp/Cntr=0.3,0.1

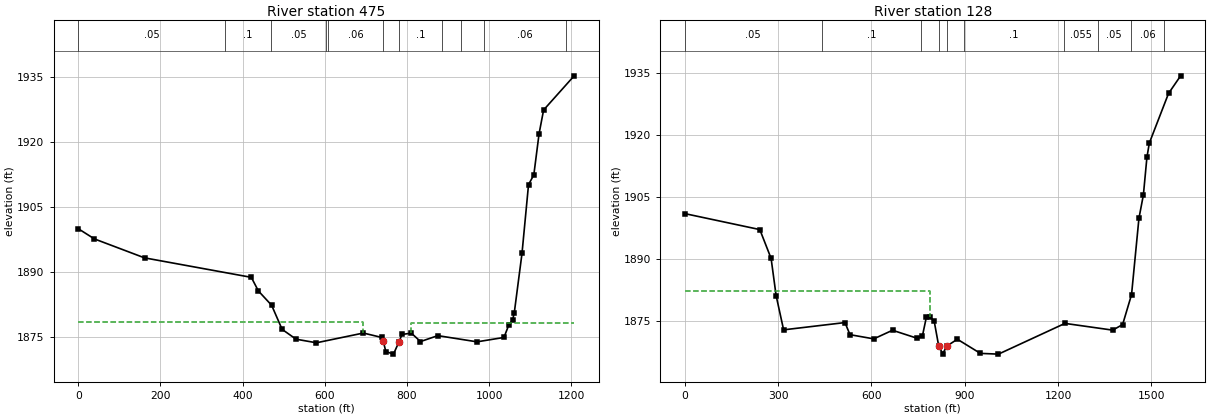
Type RM Length L Ch R = 1 ,475     ,350.5,347,340.6
XS GIS Cut Line= 4
2447957.37124272550868.691325126  2447525.670655550945.138304202
2447255.85778767551311.6341156552447375.02513741551601.682948031
#Sta/Elev= 30
       0 1899.91    39.2 1897.56   161.1 1893.19   421.1 1888.69   438.4 1885.54
   470.6 1882.24   496.1 1876.68     530 1874.41   579.7 1873.58   693.9 1875.83
   738.6 1874.81   742.2 1874.01   748.6 1871.56   767.2 1870.96   780.7  1873.8
   787.9  1875.5   810.8 1875.81     833 1873.86   875.2 1875.23   970.6  1873.8
  1036.2 1874.81  1048.3 1877.77    1057 1878.74  1061.4 1880.56  1080.1  1894.2
    1096 1910.09  1108.9 1912.35  1121.7 1921.86  1132.7 1927.33  1207.1 1935.22
#Mann= 11 ,-1 , 0
       0     .05       0  357.39      .1       0  469.61     .05       0
  603.12      .1       0     608     .06       0   742.2    .045       0
   780.7      .1       0  884.76    .055       0  932.03      .1       0
  987.47     .06       0 1188.07     .05       0
#XS Ineff= 2 , 0
          693.45 1878.33  810.34         1878.08
Permanent Ineff=
       F       F
Bank Sta=742.2,780.7
XS Rating Curve= 0 ,0
Exp/Cntr(USF)=0,0
Exp/Cntr=0.3,0.1

Type RM Length L Ch R = 1 ,128     ,,,
XS GIS Cut Line= 4
 2447826.4425791550790.6960752642447113.09561515550871.493984258
2447025.22394635551122.1451353932447355.88656701551635.579572656
#Sta/Elev= 30
       0    1901   241.2 1897.14   277.5 1890.16   293.6 1881.19   317.7  1872.9
     515 1874.66   531.1 1871.73   607.6 1870.72   667.9  1872.8   746.9 1870.87
   763.9  1871.4   776.6 1875.92   789.3 1876.06     802 1874.93   816.41868.992
   829.1 1867.16   843.6 1869.03   876.3 1870.63   950.4 1867.21  1008.5 1867.03
  1222.3 1874.46  1375.8 1872.83  1407.7 1874.18  1436.4 1881.42  1460.2 1899.88
  1474.5 1905.53  1485.8 1914.58  1493.5 1918.04  1555.3 1930.05  1594.2 1934.31
#Mann= 10 ,-1 , 0
       0     .05       0  439.74      .1       0     760     .06       0
   816.4    .045       0   843.6     .06       0   897.2      .1       0
 1220.39    .055       0  1327.1     .05       0 1433.82     .06       0
 1540.54     .05       0
#XS Ineff= 2 , 0
          789.48 1882.32
Permanent Ineff=
       F       F
Bank Sta=816.4,843.6
XS Rating Curve= 0 ,0
Exp/Cntr(USF)=0,0
Exp/Cntr=0.3,0.1
LCMann Table=0

Chan Stop Cuts=-1
Use User Specified Reach Order=0
Composite Channel Slope=5